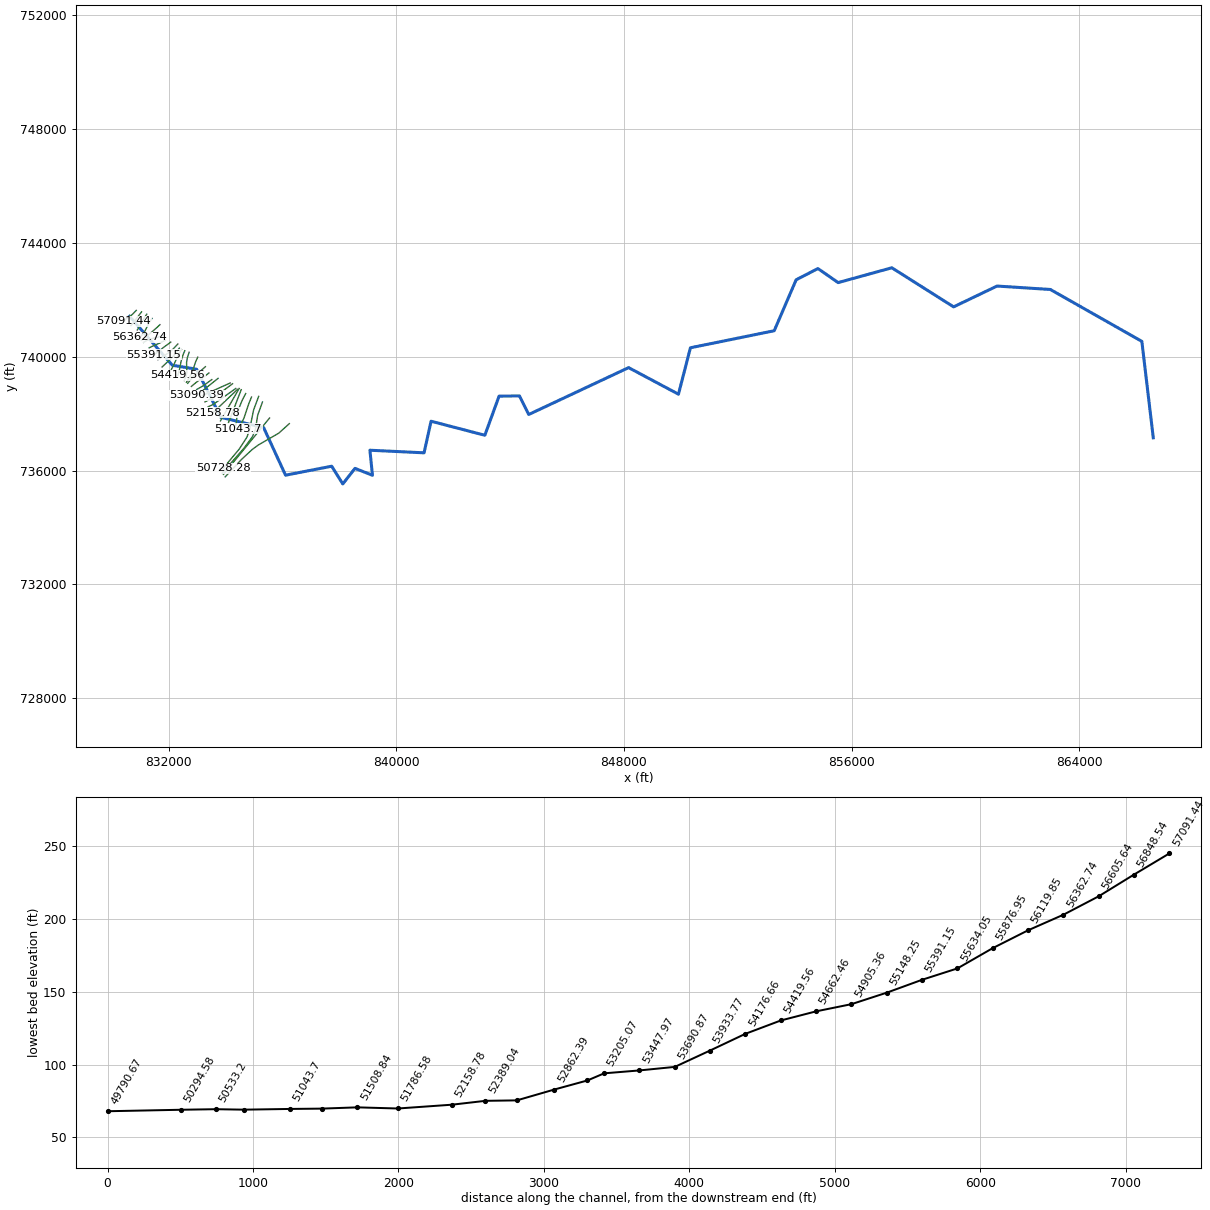
--- 8407_ras.prj (project) ---

Proj Title=8407
Current Plan=p01
Default Exp/Contr=0.3,0.1
English Units
Geom File=g01
Flow File=f01
Plan File=p01
Y Axis Title=Elevation
X Axis Title(PF)=Main Channel Distance
X Axis Title(XS)=Station
BEGIN DESCRIPTION:
RFD model 8407 exported to HEC-RAS
END DESCRIPTION:

--- 8407_ras.p01 (plan) ---

Plan Title=Plan 01
Program Version=4.10
Short Identifier=Plan 01
Geom File=g01
Flow File=f01
Subcritical Flow
Calc Critical at every XS
Secant Critical Depth

--- 8407_ras.f01 (steady flow) ---

Flow Title=Flow 01
Program Version=5.01
Number of Profiles= 6
Profile Names=10yr,25yr,50yr,100yr,100plus,500yr
River Rch & RM=8407,74,57091.44
 7702.1211873.2315695.9518928.6427635.8126665.48
River Rch & RM=8407,74,56848.54
 7711.26 11887.715715.4318952.4927670.6326695.39
River Rch & RM=8407,74,56605.64
  7731.611919.9415758.8519005.6527748.2526762.14
River Rch & RM=8407,74,56362.74
  7772.911985.2915846.7719113.2227905.3126896.82
River Rch & RM=8407,74,56119.85
 7803.9612034.5415913.1119194.46 28023.9 26998.7
River Rch & RM=8407,74,55876.95
 7807.07 12039.515919.8119202.6828035.9227009.09
River Rch & RM=8407,74,55634.05
 7823.3512065.4815954.9519245.89   2809927063.77
River Rch & RM=8407,74,55391.15
 7893.87 12177.716106.4819431.8628370.5227297.91
River Rch & RM=8407,74,55148.25
 7895.6812180.6216110.4419436.7428377.6427304.12
River Rch & RM=8407,74,54905.36
  7902.112190.9316124.4619454.0428402.8927326.18
River Rch & RM=8407,74,54662.46
 7942.1112255.4816212.3419562.6928561.5327465.27
River Rch & RM=8407,74,54419.56
 7943.2712257.3616214.9119565.8828566.1927469.39
River Rch & RM=8407,74,54176.66
 7953.5812274.0916237.7519594.1928607.5227505.84
River Rch & RM=8407,74,53933.77
 7962.1912288.0116256.7519617.7328641.8927536.08
River Rch & RM=8407,74,53690.87
 8056.2512438.7216461.0919869.4429009.38 27854.9
River Rch & RM=8407,74,53447.97
12506.8222273.9422631.4627585.9833332.2741907.47
River Rch & RM=8407,74,53205.07
 12510.722281.0822639.7727596.6133345.1141924.96
River Rch & RM=8407,74,53090.39
12511.7622283.0322642.04 27599.533348.6141929.73
River Rch & RM=8407,74,52862.39
12513.5222286.2822645.8227604.3333354.4441937.67
River Rch & RM=8407,74,52389.04
12553.6822360.2822732.0127714.4133487.4542118.94
River Rch & RM=8407,74,51786.58
12628.6522498.4422893.0327920.11   3373642457.83
River Rch & RM=8407,74, 51043.7
12944.0423079.9523572.3628788.7134785.5443891.13
River Rch & RM=8407,74,50728.28
12946.1423083.8223576.8928794.5134792.5443900.71
River Rch & RM=8407,74, 50533.2
12957.6823105.1223601.8228826.4134831.0943953.41
River Rch & RM=8407,74,50294.58
12960.4823110.2823607.8728834.1434840.4343966.19
River Rch & RM=8407,74,49790.67
12985.6623156.7323662.2528903.7434924.52 44081.2
River Rch & RM=8407,74,49174.88
13005.2423192.8523704.5528957.8734989.9344170.68
River Rch & RM=8407,74,48791.42
13017.1223214.7823730.2328990.7435029.6444225.01
River Rch & RM=8407,74,48145.43
17250.9531065.9133134.8141129.3549696.7864606.38
River Rch & RM=8407,74,47581.65
17261.8231086.1433159.5541161.5249735.6564661.14
River Rch & RM=8407,74,47256.56
17385.82 31317.233442.1341529.0950179.7965287.13
River Rch & RM=8407,74,46792.91
17396.6731337.4133466.8741561.2750218.6865341.96
River Rch & RM=8407,74,45663.18
17424.2731388.8533529.8241643.1850317.6465481.53
River Rch & RM=8407,74,44963.01
17450.2231437.2133589.0241720.2150410.7365612.82
River Rch & RM=8407,74,44294.77
   1746531464.7533622.7541764.1150463.7665687.62
River Rch & RM=8407,74,42795.89
17485.3531502.6933669.2141824.5750536.8265790.69
River Rch & RM=8407,74, 42286.5
18657.0133688.9636360.1145333.0954776.1871792.12
River Rch & RM=8407,74,40698.38
18723.6933813.5236514.2145534.3955019.4172137.66
River Rch & RM=8407,74, 39298.5
18814.24 33982.736723.6445808.0455350.07 72607.6
River Rch & RM=8407,74,39153.39
18815.8533985.7236727.3845812.9355355.9872615.99
River Rch & RM=8407,74,38153.91
19402.82 35083.138089.5247594.5757508.7375681.31
River Rch & RM=8407,74,36164.57
19472.15 35212.838250.9347805.8957764.0876045.53
River Rch & RM=8407,74,34801.76
19685.93 35612.838749.2748458.5958552.7477171.34
River Rch & RM=8407,74,33572.56
19717.6235672.1138823.2148555.4858669.8277338.59
River Rch & RM=8407,74,32124.77
19778.0835785.2838964.3948740.4858893.3577657.96
River Rch & RM=8407,74,30575.44
19913.2636038.3439280.3149154.57 59393.778373.22
River Rch & RM=8407,74, 28692.5
20015.7236230.1839520.0249468.8859773.4878916.45
River Rch & RM=8407,74,27748.19
27662.9550634.7157997.5973937.5389339.06121986.2
River Rch & RM=8407,74,26201.82
27691.5450688.8558068.6674032.4589453.76122155.9
River Rch & RM=8407,74,26075.59
27693.3250692.23 58073.174038.3889460.92122166.5
River Rch & RM=8407,74,25124.72
27719.5250741.8558138.2474125.3989566.05122322.1
River Rch & RM=8407,74,   24667
27728.16 50758.258159.7174154.0789600.71122373.4
River Rch & RM=8407,74,22758.96
27963.1351203.2358744.42 74935.390544.66123771.1
River Rch & RM=8407,74,21458.85
28047.1951362.4958953.8575215.2190882.89124272.2
River Rch & RM=8407,74,19826.99
28103.6151469.3759094.4575403.1591109.98124608.8
River Rch & RM=8407,74,17908.41
28313.0151866.1759616.8176101.5891953.89125860.1
River Rch & RM=8407,74,16313.54
28371.0951976.2459761.8176295.5192188.22126207.7
River Rch & RM=8407,74, 15069.5
28442.7652112.0859940.8376534.9792477.55  126637
River Rch & RM=8407,74,13714.58
28479.4752181.6660032.5576657.6792625.82126857.1
River Rch & RM=8407,74,12528.39
28521.2152260.7760136.85 76797.292794.41127107.3
River Rch & RM=8407,74, 10451.5
28835.9952857.5960924.4977851.3294068.11128999.1
River Rch & RM=8407,74,9323.491
 28890.652961.1461061.2878034.4594289.39  129328
River Rch & RM=8407,74,9207.989
28892.37 52964.561065.72 78040.494296.58129338.7
River Rch & RM=8407,74,7380.454
28953.7353080.8861219.5178246.3294545.39129708.6
River Rch & RM=8407,74,6150.378
28987.3653144.65 61303.878359.1994681.77129911.4
River Rch & RM=8407,74,4920.302
   2912053396.2561636.4978804.7695220.16130712.1
River Rch & RM=8407,74,3690.227
29154.1753461.0761722.2478919.6395358.95130918.6
River Rch & RM=8407,74,2460.151
38557.1871389.2385973.55  111678134941.1190724.3
River Rch & RM=8407,74,1476.091
38629.8971528.5286165.79111939.7135257.2191208.6
River Rch & RM=8407,74,       0
38701.4671665.6386355.09112197.3135568.5191685.6
Boundary for River Rch & Prof#=8407,74,1
Up Type= 0
Dn Type= 2
Boundary for River Rch & Prof#=8407,74,2
Up Type= 0
Dn Type= 2
Boundary for River Rch & Prof#=8407,74,2
Up Type= 0
Dn Type= 2
Boundary for River Rch & Prof#=8407,74,2
Up Type= 0
Dn Type= 2
Boundary for River Rch & Prof#=8407,74,2
Up Type= 0
Dn Type= 2
Boundary for River Rch & Prof#=8407,74,2
Up Type= 0
Dn Type= 2

--- 8407_ras.g01 (geometry) ---

Geom Title=8407
Program Version=4.10

River Reach=8407,74
Reach XY= 30
830619.366230344741421.917808993832121.088588178739703.069481637
832973.526875509739562.726174047833826.731667059737871.465497971
835333.236634956737509.440491485836102.433125519735837.465757389
837724.828958849736152.569924076838115.453958862735530.174090712
838543.839375529736077.049090714839158.448750506735834.531729681
839068.578958847736715.069924059840972.250833858736623.594229619
841218.318542192737734.601174049843108.943542178737241.111590728
843609.930254346738617.328824316844326.391458849738623.924090743
844652.095321048737971.068094227848163.631042186739618.715757395
849916.235208846738685.122007442850337.113651185740316.920955026
853282.120625507740915.590757483854054.256042179742707.257424036
854819.881042185743101.788674051  855530.8185422742608.299090693
857417.537292186743129.132424019859589.412292196741755.434507342
861116.756042186742487.205340744862991.756042171742366.111590711
866207.684861626740541.892840801866609.594583849737151.267840751

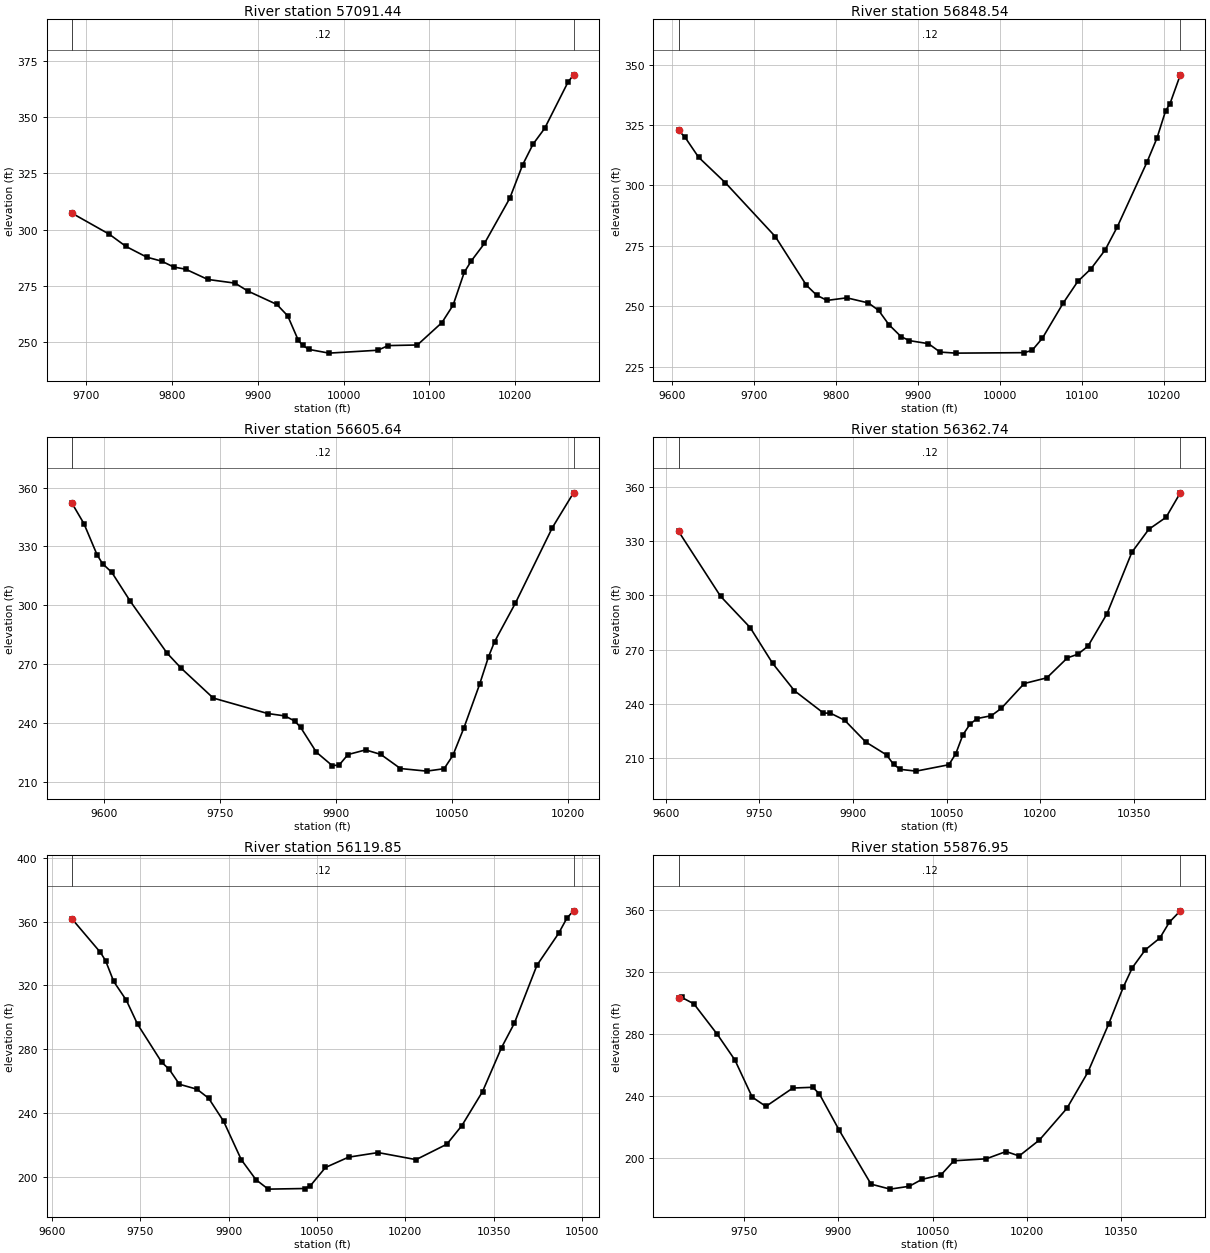
Type RM Length L Ch R = 1 ,57091.44,242.897700,242.897700,242.897700
XS GIS Cut Line= 6
  830854.5923858 741631.63960488830714.555209654741488.144923969
830655.943544487741441.282845471830591.974703647 741406.34869983
830545.934355619741374.161839289 830410.21926472741254.820793967
#Sta/Elev= 30
9682.818307.37139726.649297.95569746.042292.54529770.431287.75399787.787285.9846
9801.755283.37949815.724282.41639841.548277.85279873.411276.20799888.264272.7023
 9922.15266.73869934.833261.67059947.246 250.7449952.212248.55089959.593246.7367
9983.032245.084510039.94246.370910052.14248.440110086.14248.703510114.83 258.672
10127.83266.417310140.84281.002410148.85285.970510164.49293.898710193.93313.9101
10209.05328.861210221.11338.0036 10234.7345.037910261.88365.562510268.38368.8507
#Mann= 3 , 0 , 0
9682.818    0.12       09682.818    0.12       010268.38    0.12       0
#XS Ineff= 2 , 0
       0                               0
Bank Sta=9682.818,10268.38
Exp/Cntr=0.3,0.1

Type RM Length L Ch R = 1 ,56848.54,242.897700,242.897700,242.897700
XS GIS Cut Line= 6
831039.823952587 741578.72663942830895.282164793741390.142424674
830803.049578443741266.946454852830769.592500573741222.116500866
830678.415548304741107.231232344830666.766908708741093.577096804
#Sta/Elev= 30
9607.498 322.7749615.428319.93219631.867311.70139664.744 301.0569725.588 278.795
9763.387258.69869775.986254.55689788.586252.3954 9812.69 253.4619838.983251.3594
9851.528 248.263 9864.02242.37479878.946237.38019889.004235.74679912.317234.4833
 9926.48231.00239945.689230.567610029.21230.761310038.85231.735810051.34236.7662
10076.79251.3459 10094.5260.276410110.59265.485310127.86273.295310142.76282.9126
10178.92309.678810191.02319.563310201.61330.899310206.87333.771510219.56 345.802
#Mann= 3 , 0 , 0
9607.498    0.12       09607.498    0.12       010219.56    0.12       0
#XS Ineff= 2 , 0
       0                               0
Bank Sta=9607.498,10219.56
Exp/Cntr=0.3,0.1

Type RM Length L Ch R = 1 ,56605.64,242.897700,242.897700,242.897700
XS GIS Cut Line= 6
831223.404126827741497.920999426831143.640567268 741378.27641802
831077.197381582741269.833333352830967.615626815741066.967400138
830926.944831199740997.421630475830890.173693695740942.276133644
#Sta/Elev= 30
 9558.75 352.1979574.504341.60759591.503325.7313  9598.5321.25949610.498316.8176
9634.494302.04719681.992275.6665 9700.09 268.0459741.576252.83679811.943244.9636
9834.198243.73699846.766241.1605 9854.53237.88319874.863 225.2829895.196218.4947
9904.191218.66779915.676224.06899938.434226.43889958.098224.15149983.523216.9551
10017.36215.634610039.96216.863210051.26223.627410065.51237.619210085.78259.7893
10097.36273.873210105.13281.516910132.12301.189710179.86339.602810207.18357.3041
#Mann= 3 , 0 , 0
 9558.75    0.12       0 9558.75    0.12       010207.18    0.12       0
#XS Ineff= 2 , 0
       0                               0
Bank Sta=9558.75,10207.18
Exp/Cntr=0.3,0.1

Type RM Length L Ch R = 1 ,56362.74,242.897700,242.897700,242.897700
XS GIS Cut Line= 6
 831408.93906005 741350.53896275831332.725725029741236.844870065
831286.547673854741159.189251515831160.017451698740909.145857835
831076.729078703740790.064111742830975.640920627740678.561542115
#Sta/Elev= 30
9620.619335.29159687.826299.48749735.229282.2172 9771.29262.44229806.193247.3249
9852.596235.02769863.906234.92669886.528231.0728 9920.46219.00969953.818211.8798
9964.887206.66339975.956203.9198   10001202.9542 10053.5206.479310064.59212.5825
10075.93222.970210087.33 228.87410098.72 231.97210121.51233.5525 10137.4237.5864
10174.15251.305310210.39254.454210243.42265.508110259.93267.447310276.23271.8987
10306.82289.894510346.59323.783710373.55336.395710401.32343.062810424.15356.5627
#Mann= 3 , 0 , 0
9620.619    0.12       09620.619    0.12       010424.15    0.12       0
#XS Ineff= 2 , 0
       0                               0
Bank Sta=9620.619,10424.15
Exp/Cntr=0.3,0.1

Type RM Length L Ch R = 1 ,56119.85,242.897700,242.897700,242.897700
XS GIS Cut Line= 6
831686.683599045741128.509111969831626.439019838741071.412222554
831463.608585869740926.014605833831415.287027457740884.237584023
831295.640008543740784.302635452831036.307792912740579.219417908
#Sta/Elev= 30
9633.822361.85259682.534340.63869691.252 335.4659705.029322.45059726.452310.6847
9745.567 295.6039786.507271.80549799.193267.38169816.535257.99989846.563254.8596
9866.225249.22519891.604234.77379921.632210.67669946.503198.16589967.254192.2556
10029.07192.637610038.42194.176510064.49205.834810103.59212.285810153.81215.1751
10218.25210.752910270.45220.407510295.95232.039710331.11253.428410363.35280.9888
10385.19296.339110423.44332.606510460.08352.520710474.44362.244710485.52366.7313
#Mann= 3 , 0 , 0
9633.822    0.12       09633.822    0.12       010485.52    0.12       0
#XS Ineff= 2 , 0
       0                               0
Bank Sta=9633.822,10485.52
Exp/Cntr=0.3,0.1

Type RM Length L Ch R = 1 ,55876.95,242.897700,242.897700,242.897700
XS GIS Cut Line= 6
  831848.9832806740787.766685297 831734.59372059740728.594474662
831654.793632979740698.444917704 831335.91055426740623.856930688
831205.836207125740564.572122902831107.228304664740505.610031236
#Sta/Elev= 30
9645.003303.28769650.305 303.7479669.475299.62429706.854279.90989734.868263.3731
9762.431239.42629784.264233.42069827.208245.27559859.012245.76479869.427241.5546
9900.658218.40579951.919183.23929982.397180.009710012.85181.846810033.12186.3052
10063.57 189.23710084.08198.308710135.75199.599310167.18204.288610188.16201.4276
10220.53211.7639 10264.2232.147710297.68255.4644 10331.2286.944510354.42310.6252
10368.73323.066210389.26334.502710412.48342.129810427.75352.413410445.14359.6996
#Mann= 3 , 0 , 0
9645.003    0.12       09645.003    0.12       010445.14    0.12       0
#XS Ineff= 2 , 0
       0                               0
Bank Sta=9645.003,10445.14
Exp/Cntr=0.3,0.1

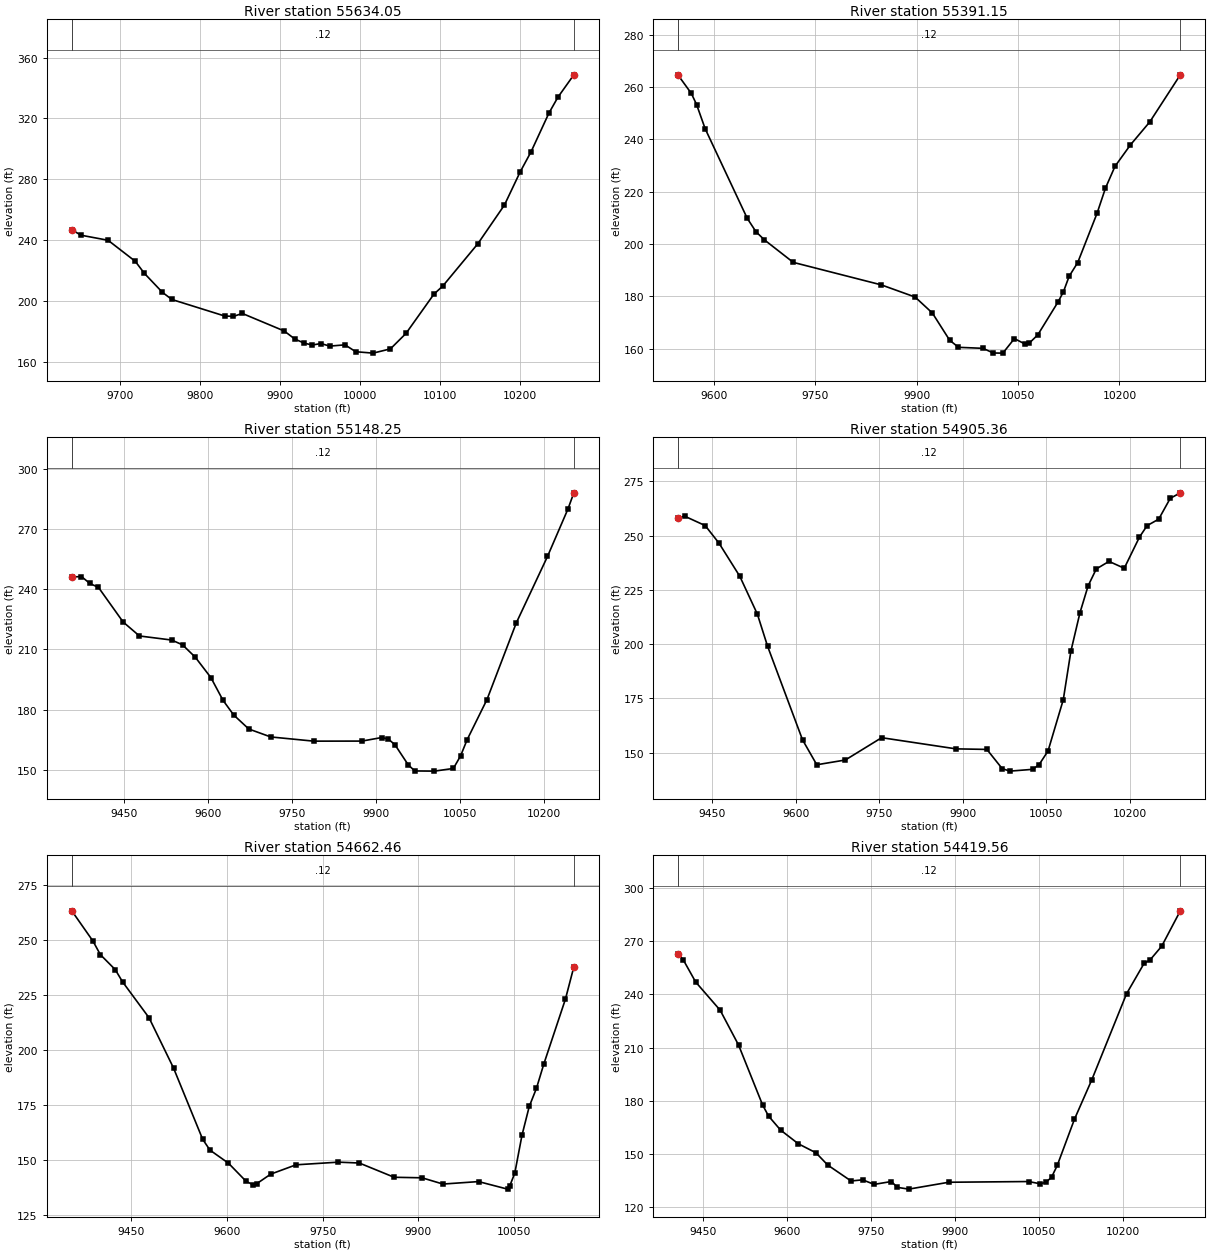
Type RM Length L Ch R = 1 ,55634.05,242.897700,242.897700,242.897700
XS GIS Cut Line= 6
831874.931544033   740584.465319831755.650672848740520.247206306
831647.725537259740469.455653665831484.295415304740399.553745861
831411.224772048740366.564394153831307.489400139740314.344453339
#Sta/Elev= 30
9639.129247.03089650.588243.44759684.613 240.1049718.637226.31979729.979218.4602
9752.662205.95289764.534201.25749830.587190.43489841.639190.17529852.691192.1151
9905.199180.60499918.612175.27659930.587172.56489940.371171.3874 9951.25172.3751
 9962.13170.67189981.362171.51379994.768166.992310016.52 166.07410038.26168.8788
10057.75179.012310092.81204.829210103.78210.061810147.67237.796610181.04263.2345
10200.64284.853310214.48298.278910236.77323.567410248.01333.964310267.97348.6506
#Mann= 3 , 0 , 0
9639.129    0.12       09639.129    0.12       010267.97    0.12       0
#XS Ineff= 2 , 0
       0                               0
Bank Sta=9639.129,10267.97
Exp/Cntr=0.3,0.1

Type RM Length L Ch R = 1 ,55391.15,242.897700,242.897700,242.897700
XS GIS Cut Line= 6
 832066.52013569740516.761000574831996.359883084740462.987545118
831796.361700908740317.613670915831659.936000071740204.955072542
831598.274922057740157.230393691831474.834841374740069.111320967
#Sta/Elev= 30
9547.732264.43279567.065257.54819574.846253.28799587.445244.09059649.714209.7977
9662.535204.71029674.898201.59759717.746192.95339847.975184.34919897.886179.7058
9923.422173.59529948.958163.21049962.052160.48549998.175 160.09710013.63158.3115
10027.59158.265510044.72163.820110060.33161.748310066.57162.074710079.22165.2286
10109.27177.846410117.15181.702110125.61187.6238 10138.3192.8834   10167211.7867
10179.33221.3418 10193.4229.647910216.32 237.88710244.87246.652810289.97264.6353
#Mann= 3 , 0 , 0
9547.732    0.12       09547.732    0.12       010289.97    0.12       0
#XS Ineff= 2 , 0
       0                               0
Bank Sta=9547.732,10289.97
Exp/Cntr=0.3,0.1

Type RM Length L Ch R = 1 ,55148.25,242.897700,242.897700,242.897700
XS GIS Cut Line= 6
 832316.39278491740449.368295251832149.111516417740273.342867341
832035.234105234740173.768157642831919.488332694740090.325249268
831766.845286908739997.471645567831616.366722943739896.683412722
#Sta/Elev= 30
9356.937246.03779374.228246.2959 9389.33242.82439404.583 240.8939448.682223.6532
9477.811216.69969535.367 214.6739554.806212.2809 9577.53206.13599605.439195.9711
9626.996184.70489646.148177.3611 9673.13170.37899712.302 166.4299789.034164.3369
9875.123164.36559910.899166.15079922.634165.32279934.369162.4741 9957.84152.5633
9969.576149.496310004.73149.408510038.52150.739710051.39156.980210063.05165.0167
10098.57185.057710150.86  223.1710206.63 256.28110243.19279.925310253.71287.9676
#Mann= 3 , 0 , 0
9356.937    0.12       09356.937    0.12       010253.71    0.12       0
#XS Ineff= 2 , 0
       09870.274                       0
Bank Sta=9356.937,10253.71
Exp/Cntr=0.3,0.1

Type RM Length L Ch R = 1 ,54905.36,242.897600,242.897600,242.897600
XS GIS Cut Line= 6
832369.076029733740304.203202375832243.885247993740134.597825481
832164.769740215740035.862941946832107.464459417 739971.18056864
832050.769916044 739913.19586725831762.059254561  739641.3995739
#Sta/Elev= 30
9389.044 258.0479400.411258.98099437.463 254.6319462.165246.55959499.538231.2852
  9531.1213.84159549.445199.03869612.153155.95079637.781144.44239689.039 146.635
9754.249 156.9139887.836151.76259943.131151.51379970.664142.65279984.431141.5083
10025.59142.3389   10037144.549810052.95150.797510080.32174.4275   10094196.7886
10110.26214.479710124.92226.889510139.57 234.65210162.41238.136610189.77234.9745
10217.14 249.35610230.82254.611310251.64257.601410272.32267.178410290.42269.7255
#Mann= 3 , 0 , 0
9389.044    0.12       09389.044    0.12       010290.42    0.12       0
#XS Ineff= 2 , 0
       09831.608                       0
Bank Sta=9389.044,10290.42
Exp/Cntr=0.3,0.1

Type RM Length L Ch R = 1 ,54662.46,242.897700,242.897700,242.897700
XS GIS Cut Line= 6
832445.622965861740253.400835462832411.318585746 740196.36327813
832325.943707635740041.431165827832249.124274168739885.821999036
 832171.80901952739710.279226887832087.528827989739553.374672208
#Sta/Elev= 30
 9356.69263.07629389.831249.35969401.501243.16389424.805236.36089436.341230.7723
9477.781214.47769516.147191.64359561.818159.25469573.236154.31359602.232148.3711
9629.783140.16599640.996138.50269646.446139.01799668.553 143.3889708.159147.6243
9774.596148.83139807.377148.43869862.012141.95829905.719141.7159  9938.5138.8724
9994.289139.999310039.68136.569310043.09137.979610051.02143.796510062.36161.0973
10073.71174.132310085.05182.4255 10096.4193.308610130.43222.934310143.62237.6014
#Mann= 3 , 0 , 0
 9356.69    0.12       0 9356.69    0.12       010143.62    0.12       0
#XS Ineff= 2 , 0
       09748.351                       0
Bank Sta=9356.69,10143.62
Exp/Cntr=0.3,0.1

Type RM Length L Ch R = 1 ,54419.56,242.897700,242.897700,242.897700
XS GIS Cut Line= 6
 832560.90922924740213.320100285 832516.30113203740113.350870996
832456.173044319739940.511273664832428.913815366739830.159279779
832369.526877038739534.034089592 832318.08430037739353.357542611
#Sta/Elev= 30
9406.568262.92489415.812259.35389437.685247.01319481.431231.09999514.241211.5044
9557.112 177.7529567.821171.46259589.238163.57689620.936155.84519652.424150.7669
9673.415143.85979715.096134.88169735.697135.53349756.298132.9654  9787.2134.5889
  9797.5 131.2989818.049130.29239889.434134.167410031.86 134.56910052.36  133.33
10062.61  134.0510072.87136.950810083.12143.623910113.87169.705310144.83191.9375
10206.76240.3409 10238.1257.489810248.59259.378710269.59 267.194 10302.8287.1255
#Mann= 3 , 0 , 0
9406.568    0.12       09406.568    0.12       0 10302.8    0.12       0
#XS Ineff= 2 , 0
       09675.697                       0
Bank Sta=9406.568,10302.8
Exp/Cntr=0.3,0.1

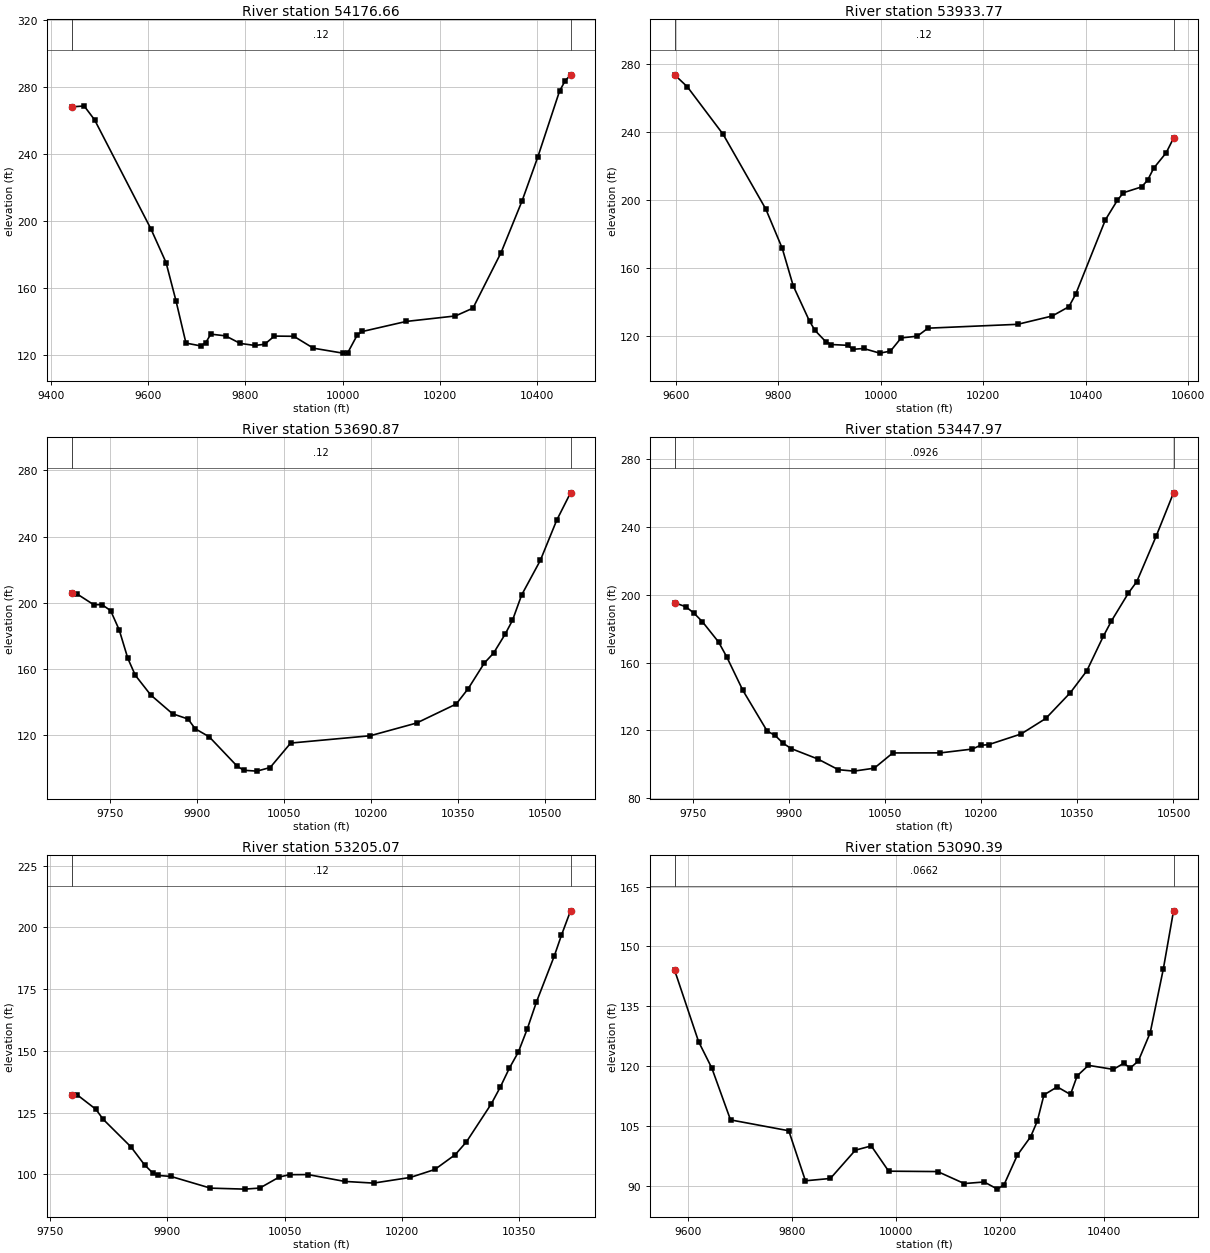
Type RM Length L Ch R = 1 ,54176.66,242.897700,242.897700,242.897700
XS GIS Cut Line= 6
832713.027306651740159.155111796832650.797674459739969.997457429
832622.417102668739801.252735651832632.550238251 739428.97224244
832595.890426002739290.309048442832538.424639494739165.226532797
#Sta/Elev= 30
9442.989 268.2869468.803268.78939490.177260.54849605.947195.40079637.084175.2745
9657.595152.35329678.024127.15759708.667125.45339718.881127.48339729.095132.4943
9759.341131.47229789.583126.9422 9819.78125.74019839.794126.44979859.808131.3349
9899.841131.20869939.909124.103210000.37 121.15210010.45121.2947 10030.6132.2125
10040.68 134.07910130.88140.084110232.03143.362210268.04148.027410325.85181.2629
10369.04212.155910401.55238.536510446.06277.764610457.46283.783810468.59287.4104
#Mann= 3 , 0 , 0
9442.989    0.12       09442.989    0.12       010468.59    0.12       0
#XS Ineff= 2 , 0
       0                               0
Bank Sta=9442.989,10468.59
Exp/Cntr=0.3,0.1

Type RM Length L Ch R = 1 ,53933.77,242.897700,242.897700,242.897700
XS GIS Cut Line= 6
833015.060066001739987.371021244832941.909046763739824.509439473
832840.630874992 739520.88964785 832798.70466893739420.008941983
832710.272529127739249.585163678832617.269510405739103.138279708
#Sta/Elev= 30
9597.788273.57169622.558266.53589692.503238.5114 9775.82194.46129807.839 171.366
9829.178149.34429861.187128.38889871.856123.00639893.196116.26579903.807114.7272
9935.195 114.2779945.658111.92489966.584 112.3979997.972109.669310018.92110.8413
10039.87 118.62110071.29119.648510092.23124.366410267.09126.631910334.69131.5409
10367.17137.001410380.29144.291410438.45188.196710461.92199.747910473.66204.1539
10508.87 207.54910520.66 211.46410532.78218.644410557.01227.654110571.39236.3035
#Mann= 3 , 0 , 0
9597.788    0.12       09597.788    0.12       010571.39    0.12       0
#XS Ineff= 2 , 0
       0                               0
Bank Sta=9597.788,10571.39
Exp/Cntr=0.3,0.1

Type RM Length L Ch R = 1 ,53690.87,242.897700,242.897700,242.897700
XS GIS Cut Line= 6
833284.880711499739651.986896295 833131.63747867739515.430524842
832969.433926005739413.704642263832888.407239162 739343.66418211
832830.791175634739279.277320825832662.663399734  739066.2499979
#Sta/Elev= 30
9682.915205.88279692.816205.30499721.155198.9143 9735.46198.96629750.328 195.337
9765.196183.67569780.064166.48519792.976156.30459819.596144.4145 9857.29133.0506
9884.004129.89159896.406124.02329920.723119.1156 9968.57101.53039980.32298.92045
 10003.198.4076210025.98 100.597 10061.4115.3549 10198.8119.770910279.02127.4615
10347.48138.956110368.19148.259310395.91163.652410412.05169.731710431.89181.0871
10444.63189.480910460.47204.806710492.76225.694610521.07249.970210544.95266.5019
#Mann= 3 , 0 , 0
9682.915    0.12       09682.915    0.12       010544.95    0.12       0
#XS Ineff= 2 , 0
       0                               0
Bank Sta=9682.915,10544.95
Exp/Cntr=0.3,0.1

Type RM Length L Ch R = 1 ,53447.97,242.897700,242.897700,242.897700
XS GIS Cut Line= 6
833408.685516799739430.688791959833258.488404436739313.915482367
833120.369391534739218.682708528833003.134954258739131.092684329
832867.408788344739022.466964296832791.447500711 738957.50893508
#Sta/Elev= 30
9721.936195.2845 9739.62192.84729752.542188.96639765.278 184.0649790.498172.0941
9803.108163.41189828.328143.62699866.159119.66539878.769116.98879891.379112.3373
9903.989109.23559945.322103.12859977.35996.8249310001.6995.9826310033.3297.72611
10062.25106.7039 10136.6106.744410186.37109.000410199.02 111.209 10211.5111.5722
10262.35117.889510300.77127.0177 10339.2142.255310364.81155.103710390.43175.3697
10403.32184.579810429.64200.9186 10442.8207.727410473.19234.6827 10500.1260.0554
#Mann= 3 , 0 , 0
9721.936  0.0926       09721.936  0.0926       0 10500.1  0.0926       0
#XS Ineff= 2 , 0
       0                               0
Bank Sta=9721.936,10500.1
Exp/Cntr=0.3,0.1

Type RM Length L Ch R = 1 ,53205.07,114.682100,114.682100,114.682100
XS GIS Cut Line= 6
833510.655720749739197.651193077833440.596382821739150.061137809
833289.389436252739038.517515675833234.806285167  739000.3824118
833159.288273272738952.903448548832976.932956123738849.194822808
#Sta/Elev= 30
9777.444 132.1639784.281132.25079808.459126.33979817.755122.29059853.349111.0946
9870.679103.8381  9881.5100.45589887.55699.529649904.43299.13513 9955.0694.38555
    999993.9845410018.1394.4184110043.0598.8851510056.1899.8365410079.7999.87659
10126.7397.1102110163.6496.4261110210.7698.7245610242.04101.946910268.28107.9899
 10282.5113.154210314.29128.5457 10325.8135.3389 10337.3142.950410348.81149.4731
10360.31158.914510371.82169.643710394.82188.429310403.87196.752810415.61206.7265
#Mann= 3 , 0 , 0
9777.444    0.12       09777.444    0.12       010415.61    0.12       0
#XS Ineff= 2 , 0
       0                               0
Bank Sta=9777.444,10415.61
Exp/Cntr=0.3,0.1

Type RM Length L Ch R = 1 ,53090.39,228.003700,228.003700,228.003700
XS GIS Cut Line= 2
833731.090876984739242.165693815832979.856295062738642.709107319
#Sta/Elev= 30
 9573.31144.01559619.483126.0949 9645.07119.43949680.995106.46759793.225103.7406
 9825.2991.189649873.38891.775049921.48798.871579952.115 99.93949985.61893.60167
10080.0593.5025810131.2290.49689 10169.690.8915610195.1989.0988710207.9990.23458
10233.5797.6337610259.16102.240710271.95 106.15610284.75112.738910310.33114.7463
10335.92112.843410348.71117.5014 10370.4120.1499 10418.5119.134110438.27120.6623
10451.06119.4827 10466.6121.246810489.44128.3325 10514.7144.3235 10534.4158.9115
#Mann= 3 , 0 , 0
 9573.31  0.0662       0 9573.31  0.0662       0 10534.4  0.0662       0
#XS Ineff= 2 , 0
       0                               0
Bank Sta=9573.31,10534.4
Exp/Cntr=0.3,0.1

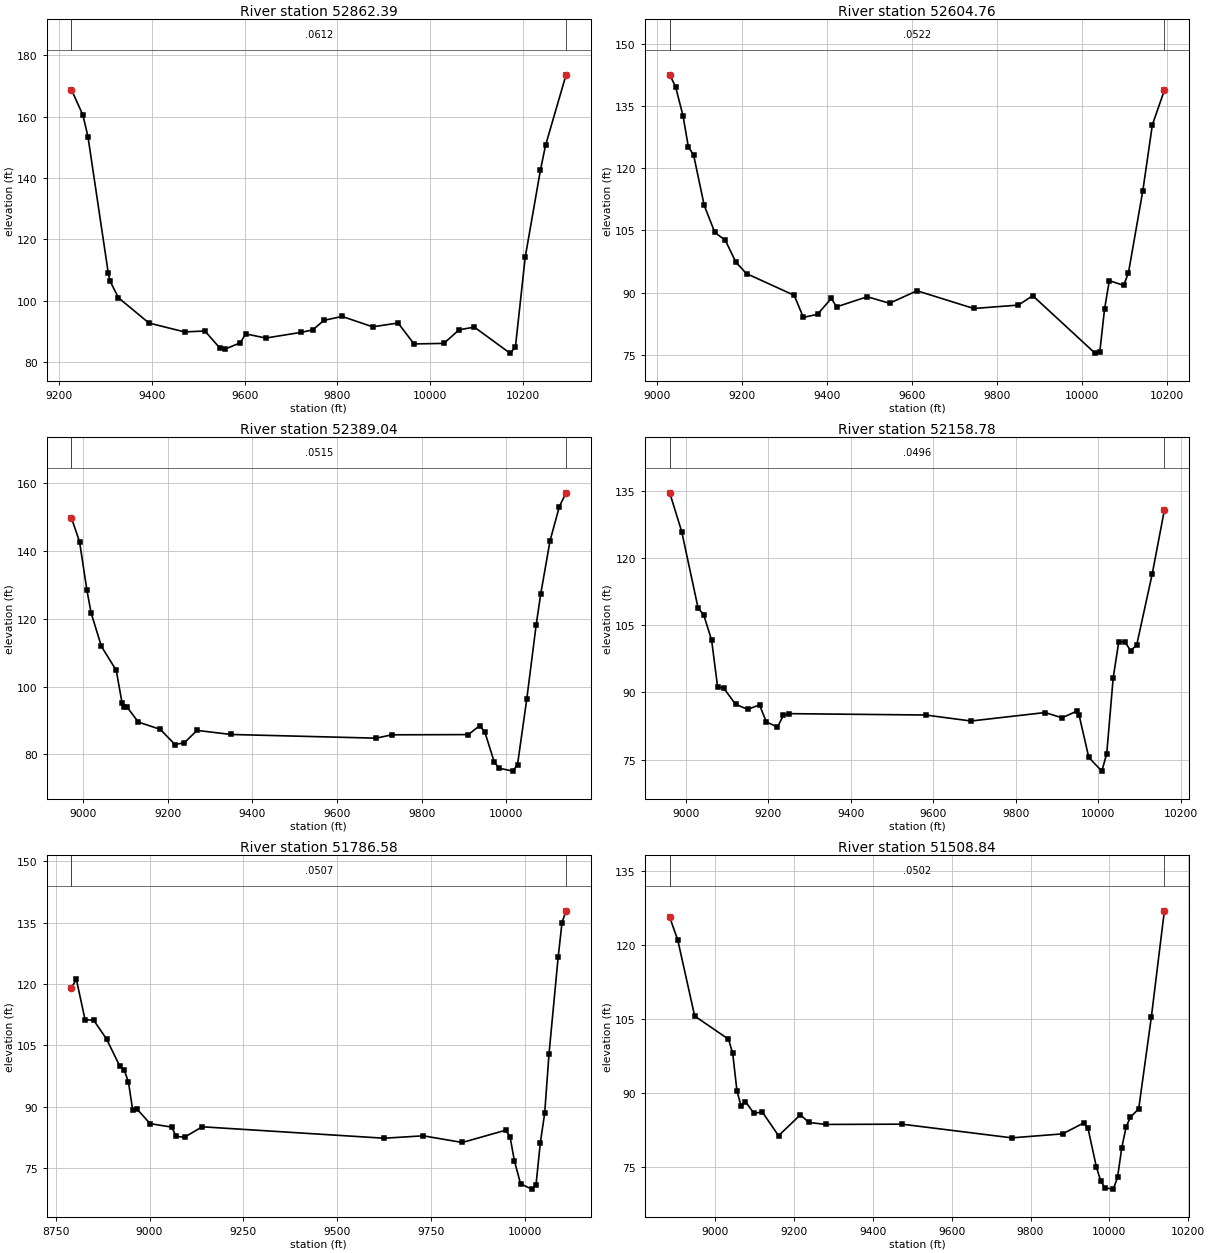
Type RM Length L Ch R = 1 ,52862.39,257.629300,257.629300,257.629300
XS GIS Cut Line= 2
834157.530283866739079.247248815833184.602009967738639.996376125
#Sta/Elev= 30
9225.895168.80289250.615160.52529261.587153.49639305.475108.94959309.124106.4023
9327.419100.9102 9393.2592.671759470.05389.768529513.94190.070629546.85784.41685
9557.82984.183739590.74486.256079601.71689.127239645.60487.777119722.40789.64991
9746.56990.413989770.87193.545619810.18394.814419876.01491.437969930.87492.67548
9965.29185.8542210029.6286.0281510062.5490.4605210095.4591.3361110172.2682.85378
10184.0184.7300110205.17114.074810238.09142.587410249.06150.602710293.38173.6204
#Mann= 3 , 0 , 0
9225.895  0.0612       09225.895  0.0612       010293.38  0.0612       0
#XS Ineff= 2 , 0
       0                               0
Bank Sta=9225.895,10293.38
Exp/Cntr=0.3,0.1

Type RM Length L Ch R = 1 ,52604.76,215.720600,215.720600,215.720600
XS GIS Cut Line= 3
834240.158304131739053.220831724833643.699815495738608.453409506
833269.946897641738413.791794576
#Sta/Elev= 30
9028.784142.52819042.536139.67329060.167132.63289072.641125.17069085.115123.1795
9110.063 111.0489135.012104.51379159.636102.64989184.90897.297899209.82294.57598
9322.12489.34779 9343.6584.022189377.10784.771419409.44388.609219421.917 86.5665
9494.20689.006869546.65887.433599611.30690.444689745.13486.171319850.27386.99313
9884.09989.2586610030.67 75.406210041.9575.5743110053.2285.99869 10064.592.89611
10098.3291.73757 10109.6 94.799210143.42114.562710165.97130.490310194.22138.7951
#Mann= 3 , 0 , 0
9028.784  0.0522       09028.784  0.0522       010194.22  0.0522       0
#XS Ineff= 2 , 0
       0                               0
Bank Sta=9028.784,10194.22
Exp/Cntr=0.3,0.1

Type RM Length L Ch R = 1 ,52389.04,230.259100,230.259100,230.259100
XS GIS Cut Line= 3
 834352.90142665738886.143491696833555.336677373738322.651770936
833380.538518632738243.390457005
#Sta/Elev= 30
8972.727149.66488992.039142.56219009.369128.36459019.134121.72129043.622111.8032
 9078.69104.74579092.59895.01381 9096.0293.879189104.84293.85099 9130.6889.54067
9182.67187.389599217.33182.926979239.52683.439499269.32287.079399349.72385.88223
9692.55684.795749729.28885.779239910.53885.846859937.43688.508719949.63886.46462
9971.59877.767089982.57875.9845410015.5275.09545 10026.576.9861710048.4696.36887
10070.42117.9666 10081.4127.272610103.36142.887610125.32  152.95 10141.2156.9961
#Mann= 3 , 0 , 0
8972.727  0.0515       08972.727  0.0515       0 10141.2  0.0515       0
#XS Ineff= 2 , 0
       0                               0
Bank Sta=8972.727,10141.2
Exp/Cntr=0.3,0.1

Type RM Length L Ch R = 1 ,52158.78,372.197100,372.197100,372.197100
XS GIS Cut Line= 3
 834414.90526117738854.999352307833587.415410873738069.050153531
833542.112685009738031.998329728
#Sta/Elev= 30
8961.109134.48468990.149 125.8569029.937108.79329043.728107.23399062.752101.6297
9077.273 91.22079091.79490.972879120.83587.345499149.87786.215679178.91887.19493
9195.43783.41952 9222.4882.263719237.00184.915989251.52185.250639581.60684.94976
 9691.9483.611639871.23285.497179912.60784.334839948.51485.800619953.98384.93767
9977.55575.4896310009.1572.4381310021.1276.3617510036.7393.2389610050.16101.1872
10064.68101.2815 10079.299.3140510093.72100.543610131.32116.360510160.89130.6351
#Mann= 3 , 0 , 0
8961.109  0.0496       08961.109  0.0496       010160.89  0.0496       0
#XS Ineff= 2 , 0
       0                               0
Bank Sta=8961.109,10160.89
Exp/Cntr=0.3,0.1

Type RM Length L Ch R = 1 ,51786.58,277.737300,277.737300,277.737300
XS GIS Cut Line= 2
834471.780276456738886.476641969833814.523235512737745.696514772
#Sta/Elev= 30
8792.125 119.106 8805.37121.12658828.452111.28978851.534111.14598885.832 106.525
 8920.7899.941258932.32199.036368943.86296.080928955.403 89.09718966.94489.39112
9001.56785.848759059.27284.994319070.81382.708169093.89582.560479140.05985.07552
 9624.7882.277619728.64982.868469832.51881.233189947.92884.238079959.46982.69741
 9971.0176.826749987.55571.1402810017.1769.8245710028.7270.8856910040.2681.19487
 10051.888.4084710063.34102.945910087.71126.636410097.96  135.05 10108.7137.9146
#Mann= 3 , 0 , 0
8792.125  0.0507       08792.125  0.0507       0 10108.7  0.0507       0
#XS Ineff= 2 , 0
       0                               0
Bank Sta=8792.125,10108.7
Exp/Cntr=0.3,0.1

Type RM Length L Ch R = 1 ,51508.84,246.952300,246.952300,246.952300
XS GIS Cut Line= 2
834544.548126627738844.011781795834092.114186478737674.262232952
#Sta/Elev= 30
8885.171125.67118905.555121.08018948.443105.67539034.218100.9853 9044.9498.08801
9055.66290.504039066.38487.372859077.10688.35755 9098.5585.984789119.99386.22951
9161.12981.430989216.49185.677559237.93584.120969280.82283.718979473.81783.77353
9752.58781.00199 9881.2581.80923 9934.8684.021359945.58282.978899967.02675.07191
9977.748 72.3278 9988.4770.8642510009.9170.6156410020.6473.0181610031.3678.99293
10042.0883.12203 10052.885.1643210074.25 86.869710106.41105.523810139.37126.9847
#Mann= 3 , 0 , 0
8885.171  0.0502       08885.171  0.0502       010139.37  0.0502       0
#XS Ineff= 2 , 0
       0                               0
Bank Sta=8885.171,10139.37
Exp/Cntr=0.3,0.1

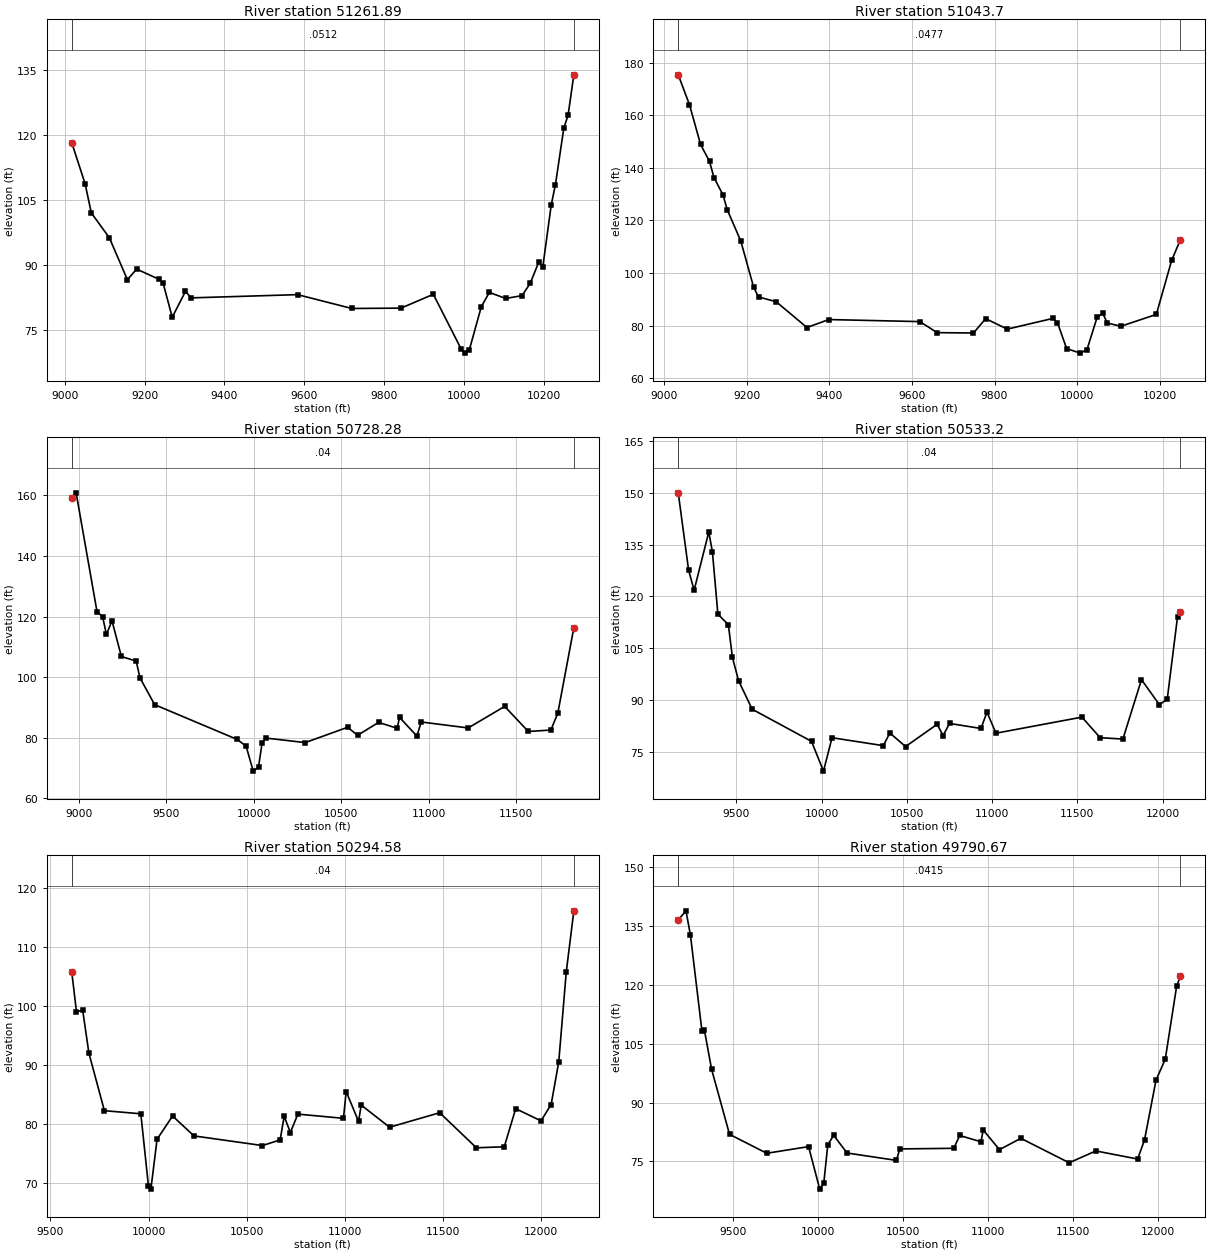
Type RM Length L Ch R = 1 ,51261.89,218.188700,218.188700,218.188700
XS GIS Cut Line= 6
834701.389835387738707.720386508834575.023888572738464.372472815
834460.120062028738178.911806279834398.899748103737941.642078674
834371.244743193737662.026685524834328.217867329737521.274784846
#Sta/Elev= 30
9017.838118.23759051.237 108.7889066.722102.07829111.86996.342269157.01586.67419
9180.23689.116119235.80386.776459246.37485.905199269.25978.005069302.35483.98085
9316.66282.479439582.95283.224639718.67780.033169841.76180.117259922.63283.30486
9992.75670.6110710002.77 69.740110012.7870.4976710042.8680.4761910062.9583.73636
10103.6882.3453310144.7783.0002910165.5385.9062510186.2890.6958310196.6689.64877
10217.72103.907710228.26108.610510249.33121.686410259.87124.566210274.33133.9066
#Mann= 3 , 0 , 0
9017.838  0.0512       09017.838  0.0512       010274.33  0.0512       0
#XS Ineff= 2 , 0
       0                               0
Bank Sta=9017.838,10274.33
Exp/Cntr=0.3,0.1

Type RM Length L Ch R = 1 , 51043.7,315.426300,315.426300,315.426300
XS GIS Cut Line= 6
834906.091829851 738584.73941965834835.861303973 738416.06917268
834789.844708277738291.867900974834643.490340991737852.107616167
834520.091567329737581.173375134834437.780357654737468.035641758
#Sta/Elev= 30
9033.774175.35219061.042163.97879087.893148.87439109.519142.43029120.332136.2835
9141.958129.79329152.772123.95479185.211112.20619216.49494.565299228.29890.88066
9270.95589.077059345.60579.265049398.43482.287599619.202 81.50859661.18577.30247
9749.099 77.17969778.563 82.6346 9831.0678.651119941.406 82.71969952.52881.12267
9974.73871.2490310007.66 69.520310023.9270.7905610048.6583.1604910062.3384.62198
10073.3880.9722710106.0679.7264110192.0884.2447110229.18104.776310250.16112.5906
#Mann= 3 , 0 , 0
9033.774  0.0477       09033.774  0.0477       010250.16  0.0477       0
#XS Ineff= 2 , 0
       0                               0
Bank Sta=9033.774,10250.16
Exp/Cntr=0.3,0.1

Type RM Length L Ch R = 1 ,50728.28,195.078100,195.078100,195.078100
XS GIS Cut Line= 6
835157.608288446738607.917039566834979.815874106738132.567549834
834831.913474424737404.526794747834739.419269574  737164.4927718
834469.200731441736749.012498709833914.134170675736085.805635316
#Sta/Elev= 30
8960.289158.94878985.208160.78629104.501121.63749136.696119.93339158.159114.1189
9190.353118.56849243.916106.82049328.735105.3029 9349.9499.817069434.04790.94018
9906.83579.453549957.31477.201079997.70469.0247910028.0270.3950210048.23 78.1771
10068.4579.9393810295.2178.4313710537.1983.4791210594.5680.8586110714.7285.09265
10820.5183.1641510834.4786.7385510933.4280.5801510958.4385.2275311226.8783.25808
11435.3790.3700411570.5582.0981311699.4382.5690711739.1988.11523 11830.9116.3362
#Mann= 3 , 0 , 0
8960.289    0.04       08960.289    0.04       0 11830.9    0.04       0
#XS Ineff= 2 , 0
       0                10539.45       0
Bank Sta=8960.289,11830.9
Exp/Cntr=0.3,0.1

Type RM Length L Ch R = 1 , 50533.2,238.614900,238.614900,238.614900
XS GIS Cut Line= 6
835291.585730796738411.291484754835123.328682778737948.067158982
835042.918773963737437.384009255834938.023655262737190.038785313
834641.506582225736787.523824642833874.089641458735912.720648042
#Sta/Elev= 30
9159.159150.00329220.017127.56199252.353121.76729338.423138.66079359.738132.8483
9391.711114.82819453.093111.80949476.973102.30629512.88595.573339592.868 87.2848
9940.80777.9801610011.0669.3480310061.25 79.027310362.3976.7240910400.0180.41051
10492.6476.4667610677.4982.9193510712.8679.6700110750.5883.1667610934.7681.70939
   1097086.4460911022.7180.3405911526.9784.9979811633.7679.0407511767.2678.64155
11876.2595.8597711980.8688.63902 12027.290.1296812087.65114.064612104.05115.5983
#Mann= 3 , 0 , 0
9159.159    0.04       09159.159    0.04       012104.05    0.04       0
#XS Ineff= 2 , 0
       0                10734.01       0
Bank Sta=9159.159,12104.05
Exp/Cntr=0.3,0.1

Type RM Length L Ch R = 1 ,50294.58,503.910300,503.910300,503.910300
XS GIS Cut Line= 2
835540.213927669737847.688330786833920.497298092735865.382947418
#Sta/Elev= 30
9608.556105.80229632.60199.03444 9664.2199.339869695.81992.049839774.84282.27046
9960.69781.743759999.43869.4830910011.9168.9567410043.5277.4283510122.5481.36362
10231.8877.9866310580.8776.3531410670.9577.31154 10691.581.3172310723.1178.56727
10761.3581.6849210993.7980.9758111007.5985.5226711070.8180.4411611084.19 83.2236
11228.8679.4654611484.5181.9237811671.3975.9765811813.6376.1416111871.9282.61135
12001.06 80.543712052.7183.3170712091.4590.5530312129.72105.799512168.44116.1909
#Mann= 3 , 0 , 0
9608.556    0.04       09608.556    0.04       012168.44    0.04       0
#XS Ineff= 2 , 0
       0                10807.42       0
Bank Sta=9608.556,12168.44
Exp/Cntr=0.3,0.1

Type RM Length L Ch R = 1 ,49790.67,615.792100,615.792100,615.792100
XS GIS Cut Line= 6
836235.498080721737649.960732319835864.489579498737315.111033588
835143.326197769 736897.82674686834933.169638512736742.719246958
 834554.67196059736391.846697662833980.579699452735778.687928827
#Sta/Elev= 30
9176.492136.61859221.926 138.932 9248.13132.7798 9316.06  108.22 9330.19108.5544
9372.57998.537219478.19881.922769697.07577.091529943.22778.7873410008.76 67.9448
10032.6969.4580810056.3579.2751710090.8181.6604510169.9377.1539710460.3175.27517
10479.4778.1975710797.4478.3593810832.3381.6263610957.1980.0200210970.7483.02412
11066.2178.0128411191.8380.9036311476.1274.6702911633.1577.6829911878.8775.62396
11919.5180.4820911987.2495.7677812041.44101.070312108.26119.662712130.06122.2127
#Mann= 3 , 0 , 0
9176.492  0.0415       09176.492  0.0415       012130.06  0.0415       0
#XS Ineff= 2 , 0
       0                10857.84       0
Bank Sta=9176.492,12130.06
Exp/Cntr=0.3,0.1