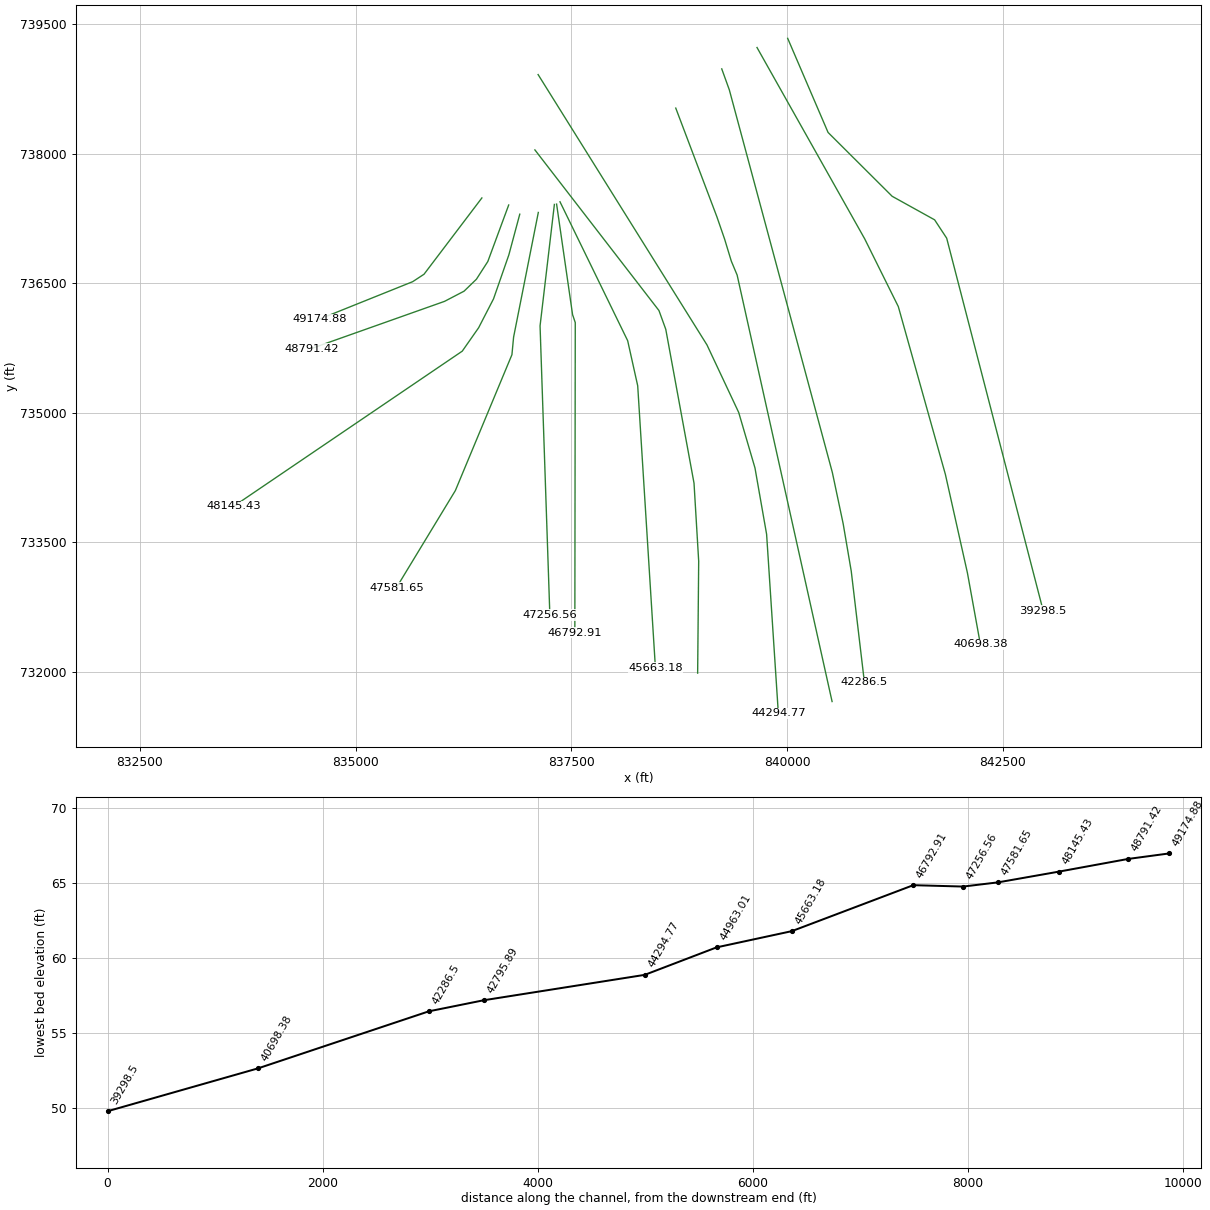
HEC-RAS study 8407_ras.prj: 8407

--- 8407_ras.g01 (geometry) --- (continued)

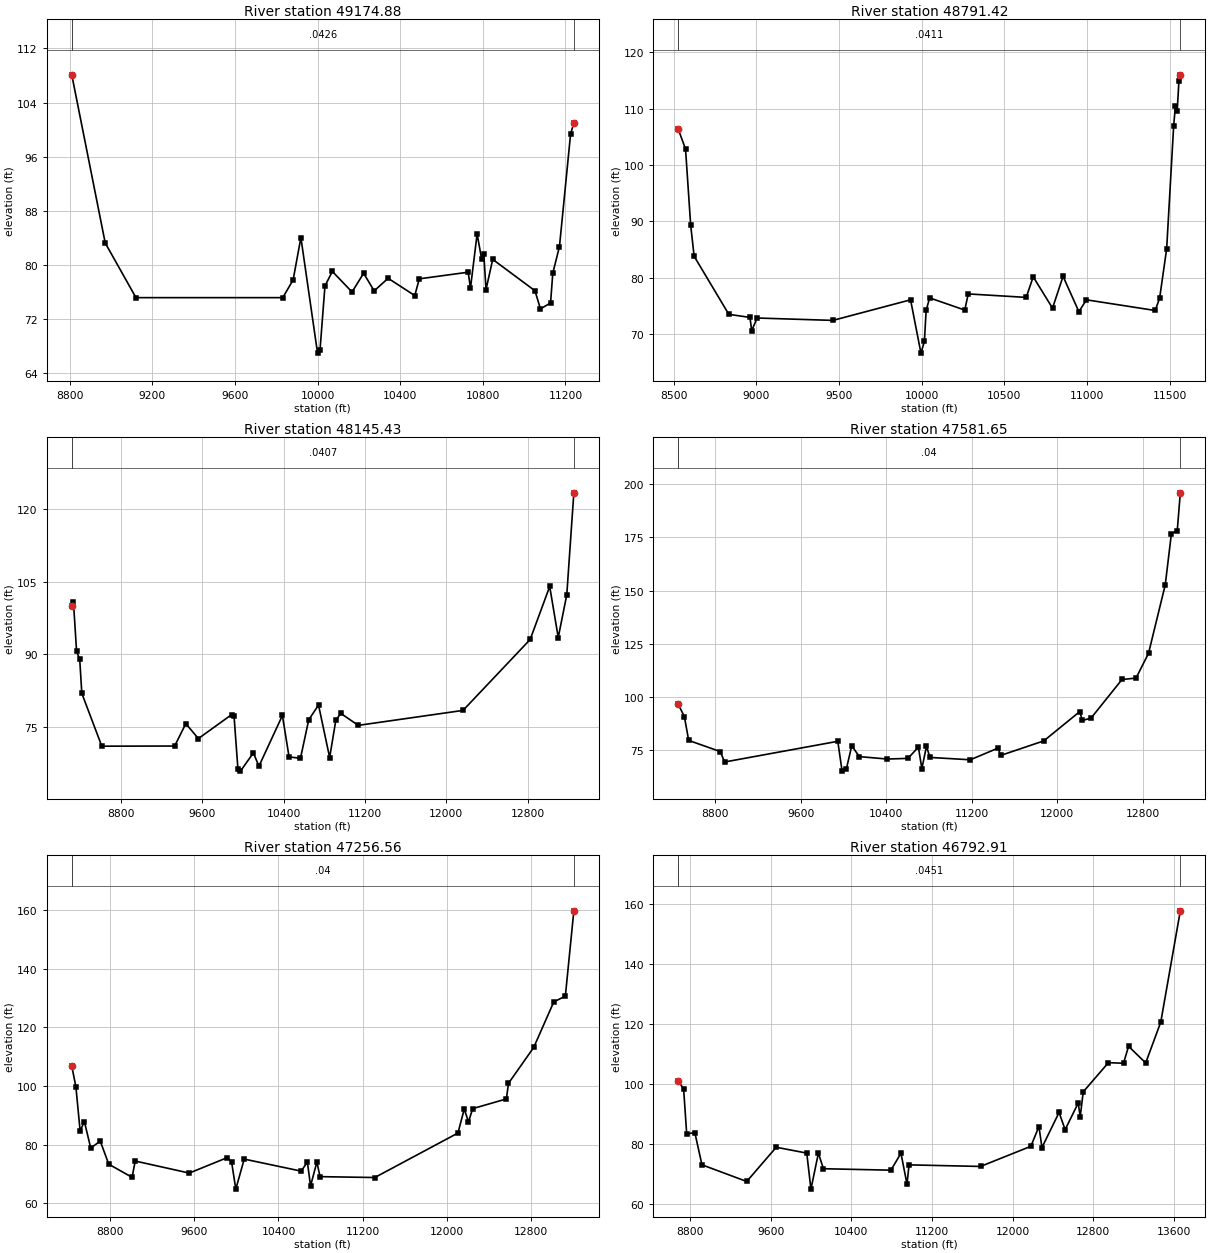
Type RM Length L Ch R = 1 ,49174.88,383.462900,383.462900,383.462900
XS GIS Cut Line= 4
836462.850111597737489.088413492835792.505176456736605.069365815
835660.655969579736518.535714757834580.356759132736084.687416491
#Sta/Elev= 30
8809.553108.09378971.497 83.2651 9120.4575.188269831.22875.188629881.428 77.8061
9919.11784.058519999.73666.99523 10011.767.4697910035.6276.91809 10071.579.06413
10166.6976.0200110222.8978.7875610274.0276.1872110341.4378.0492810470.7475.49392
10492.2977.9656910729.3778.9466810740.1576.5779110772.4884.6027110794.0380.91768
10804.8181.6148810815.5876.3782810847.9180.8382611052.6676.2042411079.0273.53028
11128.0974.3998311138.8778.79353 11171.282.7321111225.0899.3504611240.86101.0032
#Mann= 3 , 0 , 0
8809.553  0.0426       08809.553  0.0426       011240.86  0.0426       0
#XS Ineff= 2 , 0
       0                 10779.5       0
Bank Sta=8809.553,11240.86
Exp/Cntr=0.3,0.1

Type RM Length L Ch R = 1 ,48791.42,645.990000,645.990000,645.990000
XS GIS Cut Line= 6
 836773.86201994737407.480349284836531.883047813736752.541567841
836399.765721483736547.164436847836256.546373191736408.614938458
836030.415644782736290.641519195834487.195355643 735743.71582385
#Sta/Elev= 30
8528.035 106.3488572.158102.80948603.31989.320058624.09383.809378834.155 73.4994
8961.89272.963278972.57370.603929004.98972.853469463.46872.429279933.46976.07984
9996.26766.6270710017.1568.7016910027.5874.1925810048.8676.4206710261.0974.26311
10282.3477.1253510632.8476.5066110675.33 80.154110792.1774.6040410855.8980.23906
10951.4973.9916210997.6576.0779511413.0474.1867311440.0776.3787311482.56 85.1095
11525.04106.924911535.67110.530211546.29109.554911556.91114.9086 11565.2115.9703
#Mann= 3 , 0 , 0
8528.035  0.0411       08528.035  0.0411       0 11565.2  0.0411       0
#XS Ineff= 2 , 0
       0                10847.17       0
Bank Sta=8528.035,11565.2
Exp/Cntr=0.3,0.1

Type RM Length L Ch R = 1 ,48145.43,563.779000,563.779000,563.779000
XS GIS Cut Line= 6
 836902.32871374  737301.0217998836775.906673822736830.049354176
836598.285318557736319.969970598836425.473684432 735984.88579616
836235.433108905 735713.23807083833587.028800382733915.922243629
#Sta/Elev= 30
8317.11499.94937 8333.61100.83348364.49790.575058395.38488.939448415.97581.89273
8612.55770.947129329.01970.978499438.784 75.6232 9562.1772.525819888.55977.47119
9913.13977.152329951.049 66.29479976.323 65.778210103.2669.56143 10157.866.79082
10388.7477.3145210454.1368.7280310566.3968.4350410647.7176.4235210744.03 79.4646
10853.3968.5983710913.8976.2859110962.2877.7546511134.8675.2595112165.2278.36035
12825.5293.0542513017.67104.0368 13101.693.4624513185.54102.320413255.05123.4421
#Mann= 3 , 0 , 0
8317.114  0.0407       08317.114  0.0407       013255.05  0.0407       0
#XS Ineff= 2 , 0
       0                 10933.9       0
Bank Sta=8317.114,13255.05
Exp/Cntr=0.3,0.1

Type RM Length L Ch R = 1 ,47581.65,325.088900,325.088900,325.088900
XS GIS Cut Line= 5
837117.181365436737321.087633119836830.683512256735876.044022017
836811.447392168735672.481760461836155.716688014734097.462703294
835471.691283546 732970.51305257
#Sta/Elev= 30
8451.10696.484688508.28590.739978549.06479.509058844.70874.259178885.48769.35917
9945.41479.089029985.59265.0658110025.7766.1523310075.9976.9528910147.6871.88544
10407.65 70.753510602.6371.0577110700.1276.3510410732.6166.2623310775.9476.72519
10808.4471.5075911186.23  70.40411447.53 75.917811469.1972.4186711874.7479.29333
12212.0393.0868712235.4288.8761112317.3190.01129 12607.1108.158712738.43108.8109
12855.41120.457513011.83152.620913069.64176.723413124.47178.181713153.11195.9364
#Mann= 3 , 0 , 0
8451.106    0.04       08451.106    0.04       013153.11    0.04       0
#XS Ineff= 2 , 0
       0                               0
Bank Sta=8451.106,13153.11
Exp/Cntr=0.3,0.1

Type RM Length L Ch R = 1 ,47256.56,463.652100,463.652100,463.652100
XS GIS Cut Line= 3
837303.496812462737413.932640619837137.432858752736006.569748372
837251.000670105732654.275678137
#Sta/Elev= 30
8435.599106.80398474.801 99.70288515.07984.635178555.35687.861368615.77378.81408
8706.39781.175548786.95273.301399008.47868.811749038.68674.373229552.22470.26664
 9914.3375.558919954.35374.060429994.37664.7853310074.4275.0371510614.7370.93344
10674.77 73.988610704.7865.8966110764.8274.0260810794.8369.0464911315.1368.74688
12105.5983.9303112165.6292.1491412205.6487.7188612245.6792.2635912565.8595.56944
12585.86100.8971   12826113.181813016.11128.684613126.17130.671613206.94159.7773
#Mann= 3 , 0 , 0
8435.599    0.04       08435.599    0.04       013206.94    0.04       0
#XS Ineff= 2 , 0
       0                               0
Bank Sta=8435.599,13206.94
Exp/Cntr=0.3,0.1

Type RM Length L Ch R = 1 ,46792.91,1129.730000,1129.730000,1129.730000
XS GIS Cut Line= 6
837329.077693681737418.108367558837514.741988304736133.631415129
837522.001496871736114.143238945837522.687376833736112.264524294
837545.540818145736044.216555187837540.552089722732451.172487916
#Sta/Elev= 30
8680.378100.96478734.03898.18607 8764.3583.283418845.18183.692498915.90972.97812
9360.481 67.42169653.49578.825159956.61376.876339998.08664.8771510071.9676.85009
   1012271.67395   1079271.18979   10892 76.8116   1095266.52562   1097272.96077
   1168272.43167   1218279.14628   1226285.73272   1229278.72726   1246290.42104
   1252284.68373   1265293.55911   1267289.02253   1270297.29528   12952107.0023
   13102106.8129   13152112.4529   13322106.9043   13472120.554913665.83157.5797
#Mann= 3 , 0 , 0
8680.378  0.0451       08680.378  0.0451       013665.83  0.0451       0
#XS Ineff= 2 , 0
       0                               0
Bank Sta=8680.378,13665.83
Exp/Cntr=0.3,0.1

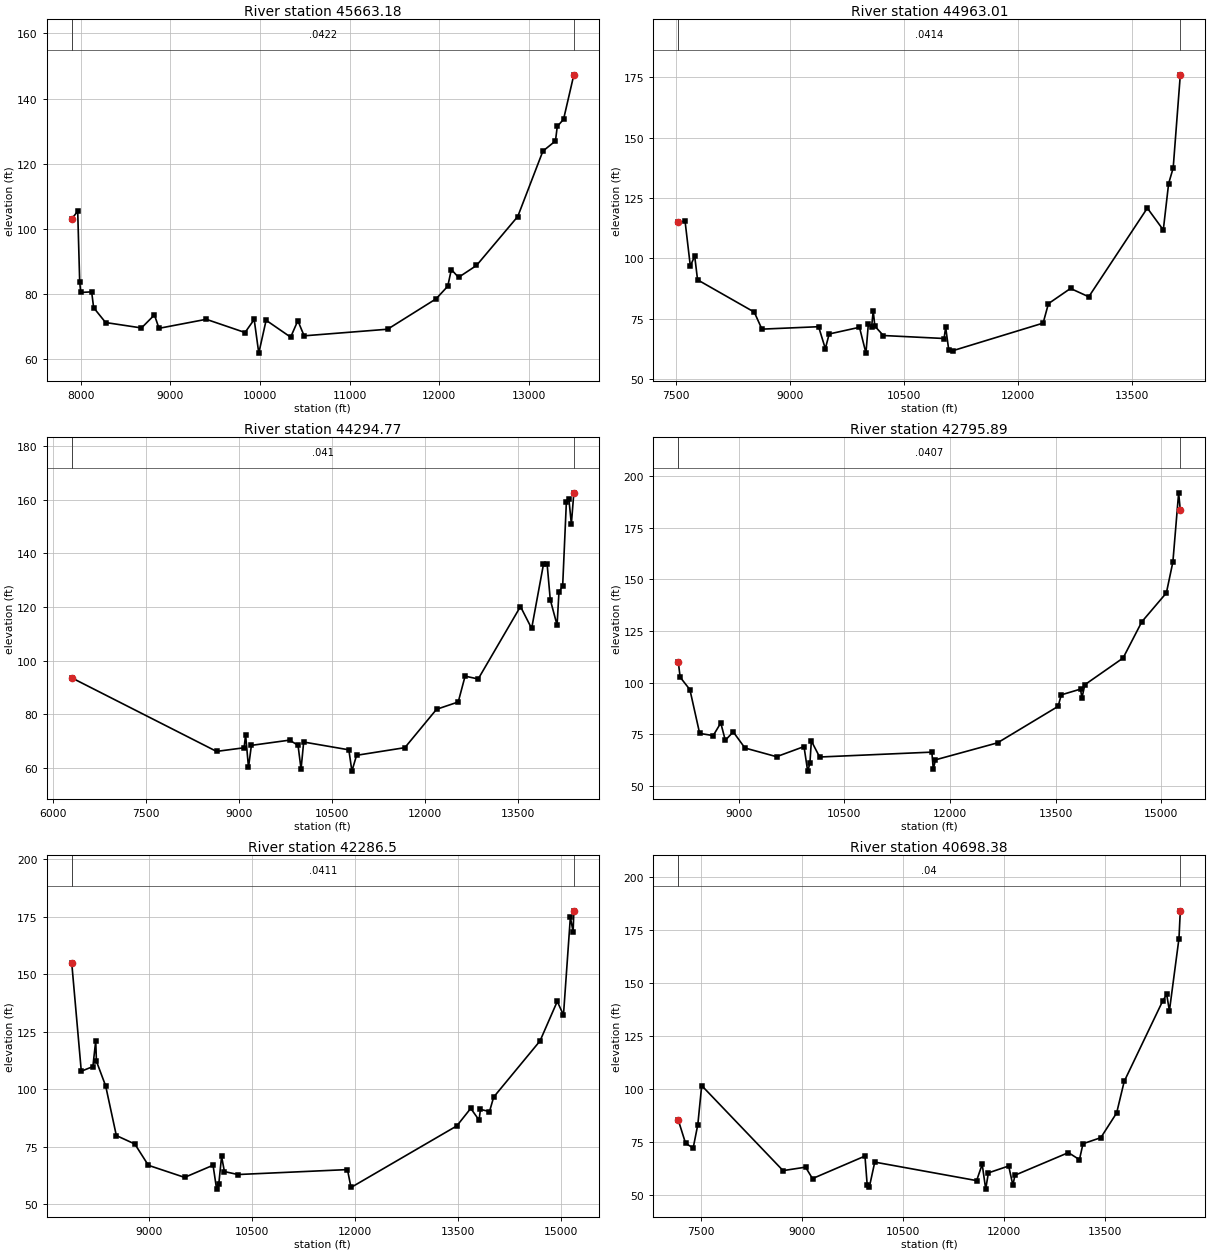
Type RM Length L Ch R = 1 ,45663.18,700.166700,700.166700,700.166700
XS GIS Cut Line= 4
837368.630086072737444.479408244838152.931106847735834.399156107
  838269.2438899735311.882392112838474.700579591732040.240176206
#Sta/Elev= 30
7899.534103.03477965.695105.42827987.94183.769767999.06580.449958121.42180.63573
8143.66875.770918277.148 71.21268677.58869.548118822.19173.552678873.14669.43283
9400.60572.203499833.29168.143399935.73872.146079986.96261.8123810068.9271.90968
 10342.966.7155810423.0671.7780610493.1967.1266211425.0369.1557411966.0978.49112
12096.3582.3582112136.4287.4900612216.5885.0873912416.9888.7342112877.88103.7817
13158.43123.871213298.71126.991713318.75131.436913388.89133.634913503.87147.3034
#Mann= 3 , 0 , 0
7899.534  0.0422       07899.534  0.0422       013503.87  0.0422       0
#XS Ineff= 2 , 0
       08292.683                       0
Bank Sta=7899.534,13503.87
Exp/Cntr=0.3,0.1

Type RM Length L Ch R = 1 ,44963.01,668.240700,668.240700,668.240700
XS GIS Cut Line= 6
837077.676182722738046.023208778838515.482656449736184.294831448
838594.561928474735966.630463847838921.982634975734183.222255097
 838976.09165575733278.938476361838964.028536183731981.351838516
#Sta/Elev= 30
7534.944114.84367624.682115.38767694.16996.724467751.033101.00537788.93891.09807
8534.40577.729148635.48570.665539380.95371.674459469.39862.569529519.93868.65977
9918.41371.4330510003.5360.7299510035.4572.9619210078.0171.7130810099.2978.23668
10120.4971.90899 10232.268.0243711031.2166.7889311051.6771.4907811092.5862.02148
11153.6961.8130912333.2573.1619112403.4181.2259512693.7287.51965 12933.8 84.0661
13703.87120.807713913.94111.755513983.97130.9684   14044137.426314137.72176.0045
#Mann= 3 , 0 , 0
7534.944  0.0414       07534.944  0.0414       014137.72  0.0414       0
#XS Ineff= 2 , 0
       0 9126.46                       0
Bank Sta=7534.944,14137.72
Exp/Cntr=0.3,0.1

Type RM Length L Ch R = 1 ,44294.77,1498.882500,1498.882500,1498.882500
XS GIS Cut Line= 6
837114.819171216738919.205530932839071.868056759735786.156937448
839439.883228118735002.889900669839628.304720679  734360.6185253
839763.281361092733591.639535962839899.418593828731514.813426226
#Sta/Elev= 30
6303.11293.627118637.51666.241819082.34267.602729105.75472.471549152.57760.30344
9199.40168.493359815.03770.441649951.27968.51655 10000.259.6587110042.4769.73399
10770.7266.8335710820.11 58.897910895.1264.7911611673.8167.6366312185.0681.92853
12534.5184.6486412645.2194.2763612856.2493.2149813538.01120.203613718.23112.0235
13908.37135.855613968.41135.886614018.43122.760714128.46113.263214158.47125.5015
14218.49127.936514278.51159.273314318.51160.270214358.52150.901414398.71162.5449
#Mann= 3 , 0 , 0
6303.112   0.041       06303.112   0.041       014398.71   0.041       0
#XS Ineff= 2 , 0
       08574.213                       0
Bank Sta=6303.112,14398.71
Exp/Cntr=0.3,0.1

Type RM Length L Ch R = 1 ,42795.89,509.393300,509.393300,509.393300
XS GIS Cut Line= 6
838710.294491308738530.850702891839187.396039338737269.997830042
 839276.40849038737012.567301025839354.466984213736756.043788758
 839421.73559474736595.524500136840522.303357674731651.894872484
#Sta/Elev= 30
8142.744110.09028170.213102.6129 8308.3596.602998446.76475.439768639.23674.39494
8746.55680.504668810.94772.10288  8923.176.194759089.97968.382099538.522 64.1847
 9928.27 69.06659980.38457.2033510011.6660.9323810032.55 71.785210150.2464.02903
11743.0666.3897711763.5558.1905511794.2962.6637612675.3470.87999 13535.988.53569
13580.1894.0765513853.4996.8629613873.9892.5840313914.9698.9887214457.94111.8863
 14724.3129.431515072.63143.373415164.83158.304215246.79191.774415270.46183.3713
#Mann= 3 , 0 , 0
8142.744  0.0407       08142.744  0.0407       015270.46  0.0407       0
#XS Ineff= 2 , 0
       09122.626                       0
Bank Sta=8142.744,15270.46
Exp/Cntr=0.3,0.1

Type RM Length L Ch R = 1 , 42286.5,1588.117700,1588.117700,1588.117700
XS GIS Cut Line= 6
839243.349988744738985.402739151839331.207878684738742.119705598
840525.478580181734306.472911081840650.623676841733713.921534942
840744.395657611733163.365483323840897.113962476731874.442966783
#Sta/Elev= 30
7868.223 154.6578006.869107.75698175.701109.77168217.141120.96378227.501112.0998
8362.181101.33468517.58279.770838786.94376.093058983.78366.833139512.145 61.5714
9926.54766.860289978.34756.4663210009.4358.5607210050.8770.6619610092.3164.10045
10289.1562.8162911884.5964.9632711936.3957.1880413477.6183.9687913680.55 91.5893
13802.0786.4970413822.3291.1691813953.8390.1827114014.4796.4894514689.92120.9185
14941.28138.120215031.72132.184615132.15174.7397 15172.3168.425115182.89 177.524
#Mann= 3 , 0 , 0
7868.223  0.0411       07868.223  0.0411       015182.89  0.0411       0
#XS Ineff= 2 , 0
       09163.486                       0
Bank Sta=7868.223,15182.89
Exp/Cntr=0.3,0.1

Type RM Length L Ch R = 1 ,40698.38,1399.881500,1399.881500,1399.881500
XS GIS Cut Line= 6
839652.118698137739232.803848654 840900.27314164737015.227567294
841290.005800187736229.938584191841835.506696548734285.277970075
842091.420550221733141.286398047842241.127203088732315.310751011
#Sta/Elev= 30
7168.55285.337857277.70574.298177390.30772.087047459.34583.181367516.876101.5793
8725.03561.408739058.71763.042759162.27357.642049941.24368.279869973.828 54.8077
10007.6453.8405110086.5565.4290711599.2556.6921211682.1464.3886111733.9552.66503
 11773.960.3419112075.4863.59496 12137.554.5157312168.5159.2363812961.8969.90813
13125.9266.5922513178.9674.1147113443.3876.9733613678.3588.6520113790.71103.5582
14360.31141.428414421.27144.677314461.91136.895914603.82171.056214623.78184.1372
#Mann= 3 , 0 , 0
7168.552    0.04       07168.552    0.04       014623.78    0.04       0
#XS Ineff= 2 , 0
       08946.381                       0
Bank Sta=7168.552,14623.78
Exp/Cntr=0.3,0.1

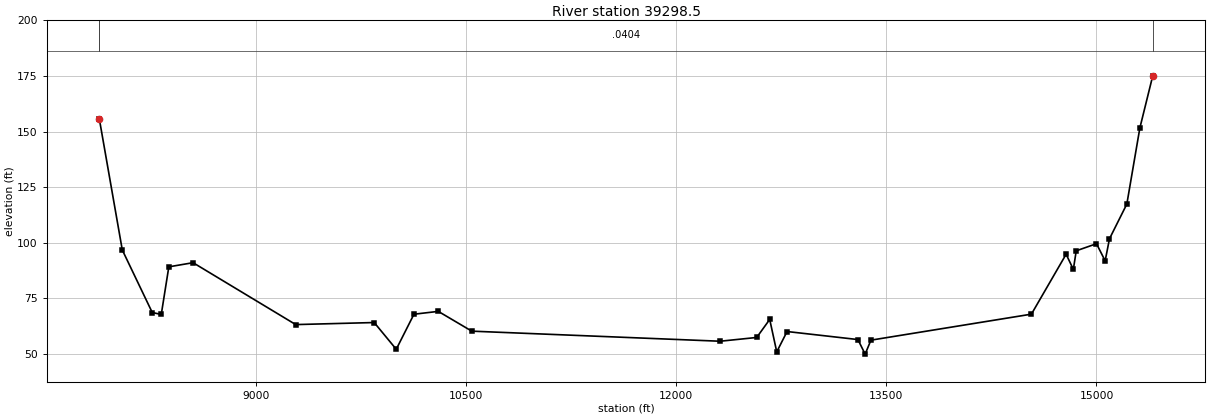
Type RM Length L Ch R = 1 , 39298.5,145.103700,145.103700,145.103700
XS GIS Cut Line= 6
840007.633897455739339.305673764840475.645029535738248.558662678
841218.948015086737508.204738628841710.824634355737235.545620357
841850.671616337  737022.7907858 842968.91352196732705.844627729
#Sta/Elev= 30
7882.221155.63358046.00396.690458259.852 68.5405 8324.2867.661698378.21889.09032
8551.14290.960939284.12563.102279844.31164.0240910001.6351.9890810128.0267.76689
10301.6769.0456710540.8960.1430412313.3755.6106612574.5857.3056912667.47  65.423
12717.6450.8253712791.3259.9787913297.0356.3651813348.6449.8062713389.9256.09224
14535.5267.7937114783.2294.7641814834.8287.9504214855.47 96.306114999.9699.50088
15061.8891.7888515092.84101.735215216.69117.352315309.58 151.58515401.59175.0593
#Mann= 3 , 0 , 0
7882.221  0.0404       07882.221  0.0404       015401.59  0.0404       0
#XS Ineff= 2 , 0
       09846.288                       0
Bank Sta=7882.221,15401.59
Exp/Cntr=0.3,0.1