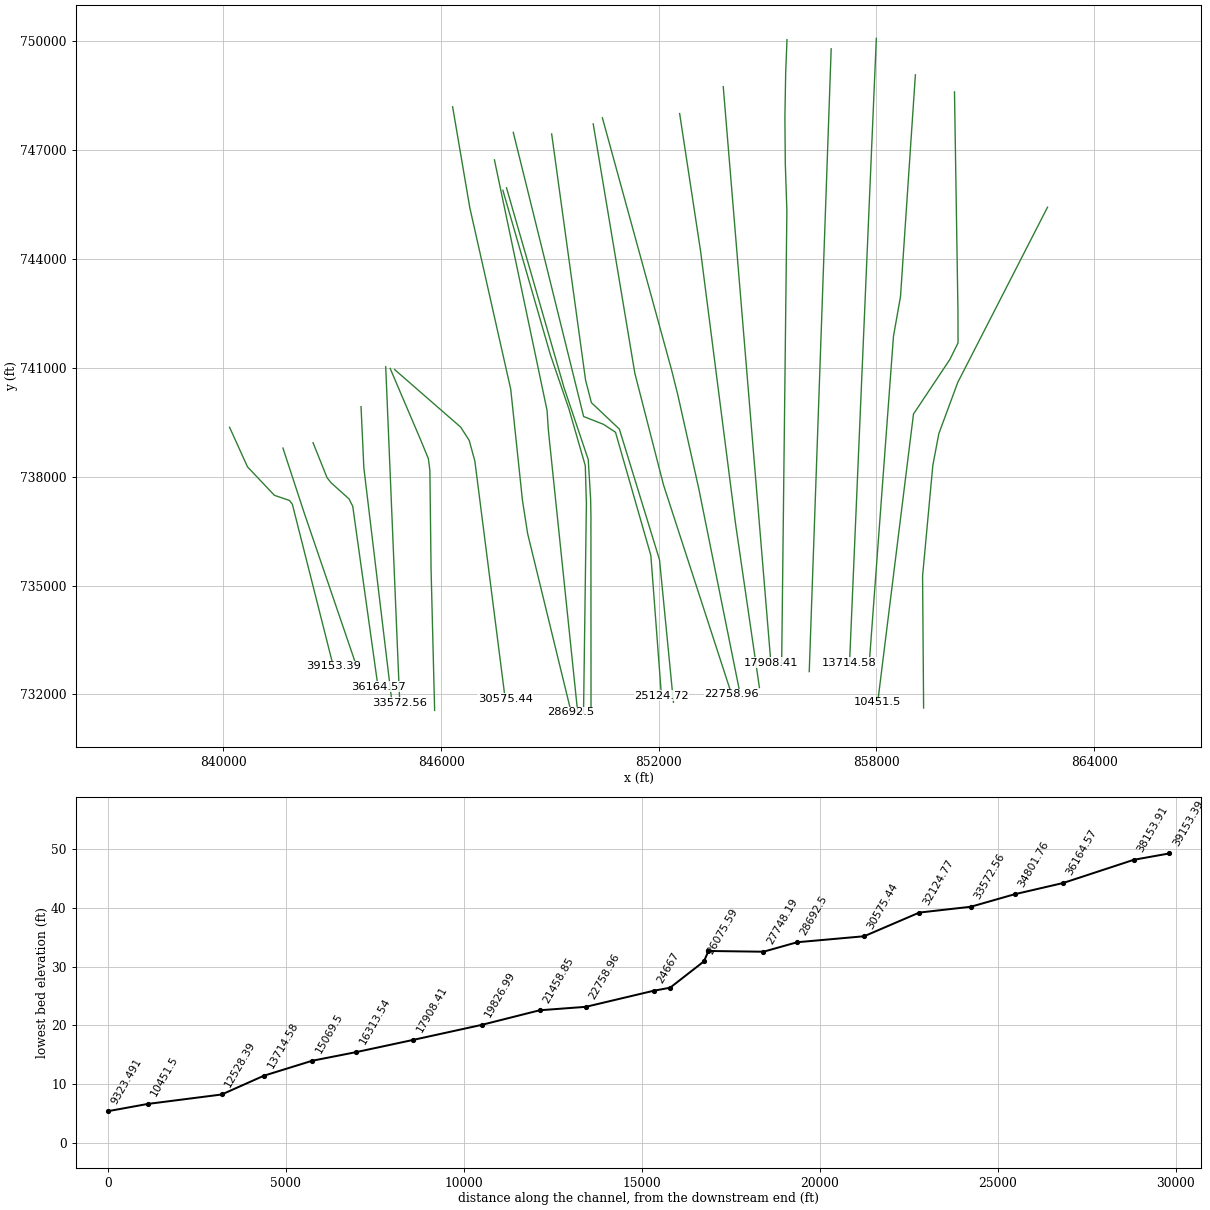
HEC-RAS study 8407_ras.prj: 8407

--- 8407_ras.g01 (geometry) --- (continued)

Type RM Length L Ch R = 3 ,39236.34,,,
BEGIN DESCRIPTION:
END DESCRIPTION:
Bridge Culvert--1,0,-1,-1, 0
Deck Dist Width WeirC Skew NumUp NumDn MinLoCord MaxHiCord MaxSubmerge Is_Ogee
47.551850,50.000000,2.6,0, 29, 28, , , 0.95, 0, 0,0,,
 9634.91 9762.04 9775.60 9789.15 9804.13 9843.38 9846.63 9867.78 9867.7810094.78
10094.7810117.9110124.3010148.3710163.0510192.4210238.2510302.2010359.6310371.11
10382.6010458.5410469.1810501.3210512.0310558.2710644.8810655.0510656.41
   65.22   68.25   68.68   68.99   69.17   70.16   70.23   70.24   70.24   70.36
   70.36   70.37   71.17   70.59   70.41   69.80   69.20   67.43   66.36   66.07
   65.93   64.18   63.85   63.21   63.18   62.43   61.86   61.73   61.73
 -934.78 -931.75 -931.32 -931.01 -930.83 -929.84 -929.77 -929.76   65.74   65.86
 -929.64 -929.63 -928.83 -929.41 -929.59 -930.20 -930.80 -932.57 -933.64 -933.93
 -934.07 -935.82 -936.15 -936.79 -936.82 -937.57 -938.14 -938.27 -938.27
 9634.91 9762.04 9775.60 9789.15 9804.13 9846.63 9905.77 9905.7710117.9110124.30
10132.7710132.7710148.3710163.0510192.4210238.2510302.2010359.6310371.1110382.60
10458.5410469.1810501.3210512.0310558.2710644.8810655.0510656.41
   65.22   68.25   68.68   68.99   69.17   70.23   70.26   70.26   70.37   71.17
   70.95   70.95   70.59   70.41   69.80   69.20   67.43   66.36   66.07   65.93
   64.18   63.85   63.21   63.18   62.43   61.86   61.73   61.73
 -934.78 -931.75 -931.32 -931.01 -930.83 -929.77 -929.74   65.76   65.87   66.67
   66.45 -929.05 -929.41 -929.59 -930.20 -930.80 -932.57 -933.64 -933.93 -934.07
 -935.82 -936.15 -936.79 -936.82 -937.57 -938.14 -938.27 -938.27
Pier Skew, UpSta & Num, DnSta & Num=  ,9942.78, 2 ,9980.77, 2 , 0 , 0 , 0 ,,
    4.00    4.00
 -929.72   70.28
    4.00    4.00
 -929.70   70.30
Pier Skew, UpSta & Num, DnSta & Num=  ,10019.78, 2 ,10057.77, 2 , 0 , 0 , 0 ,,
    4.00    4.00
 -929.68   70.32
    4.00    4.00
 -929.66   70.34
BR Coef=-1 , 0 , 0 ,, 0 ,,,0.8,0,1,0,
WSPro=,,,, 1 ,,,, 0 ,,,, 0 ,,,,-1 ,-1 ,-1 , 0 , 0 , 0 , 0 , 0
BC Design=,, 0 ,, 0 ,,,,,,

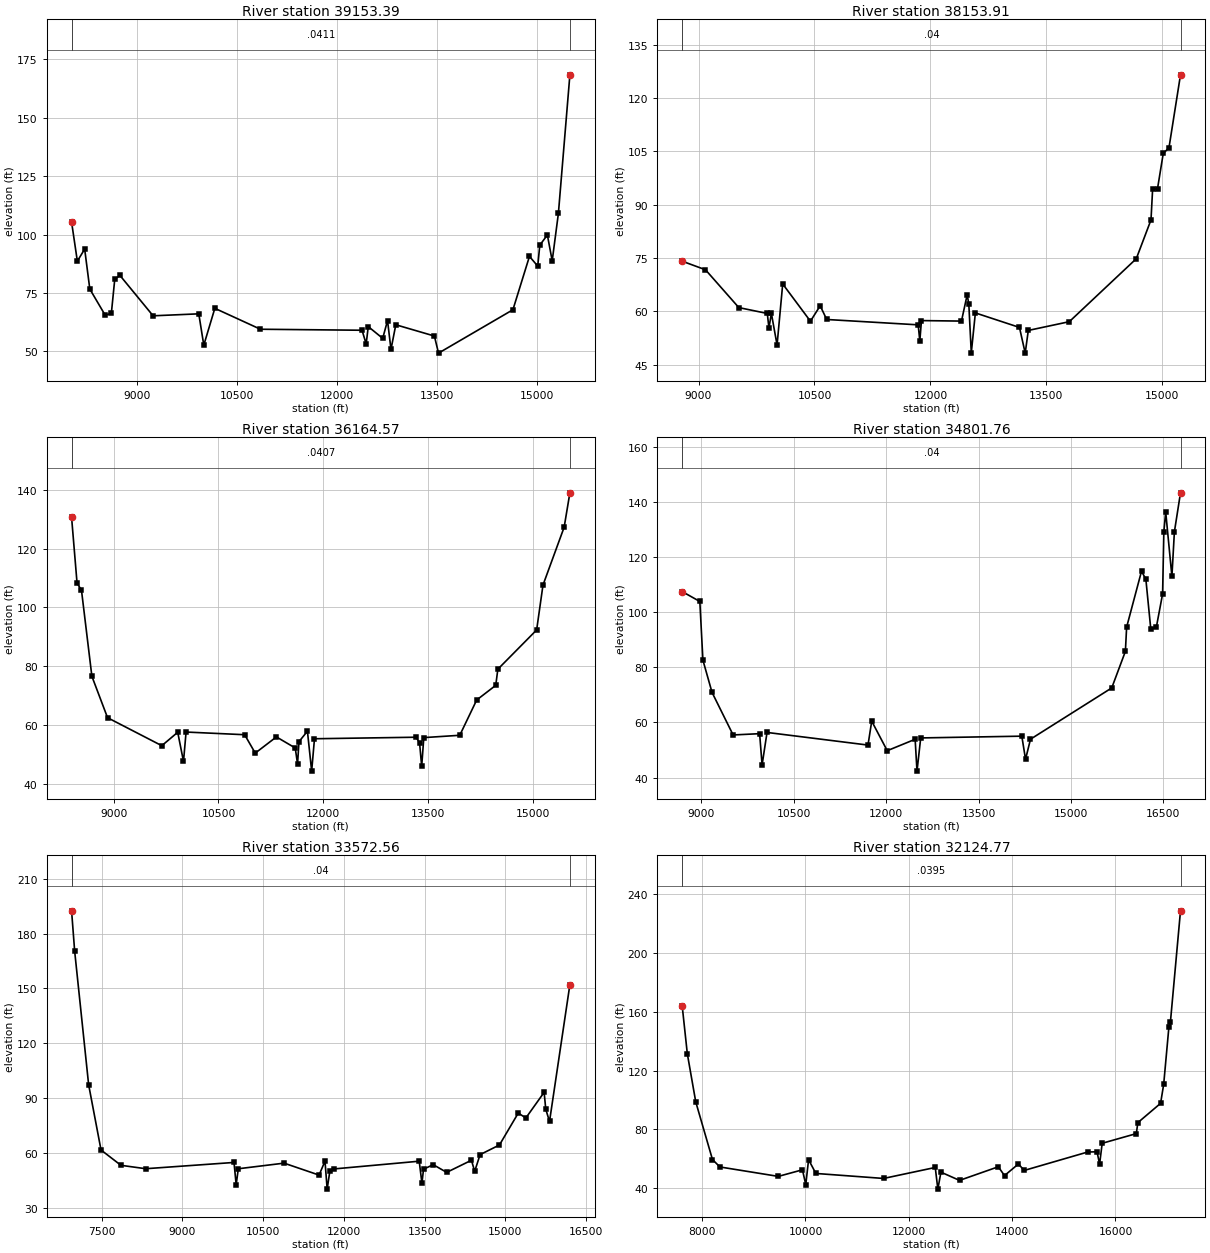
Type RM Length L Ch R = 1 ,39153.39,999.481500,999.481500,999.481500
XS GIS Cut Line= 6
840169.242247516 739363.56016706840663.805116381738272.079967413
841405.999528772 737487.82459123841818.782753531737347.478956784
841898.844553879737245.585140545843028.146582228732778.234429065
#Sta/Elev= 30
 8025.79 105.3488112.03888.645588221.82593.796778298.67676.703138529.22865.50474
8621.24866.33144 8671.9580.845128748.80182.56309 9246.38 65.25739930.16866.10409
10005.1152.6938610170.3168.46078 10853.459.51245 12374.359.0820712436.1953.19791
12467.1360.6454212683.7455.6169512755.94 63.225312807.5150.8941512879.7261.42549
13457.3356.6082813519.2249.2945514633.1967.8519214880.7490.6809715004.5286.51184
15035.4695.4768415148.9299.8407915221.1288.7767815313.95 109.08315485.96168.3384
#Mann= 3 , 0 , 0
 8025.79  0.0411       0 8025.79  0.0411       015485.96  0.0411       0
#XS Ineff= 2 , 0
       09907.103                       0
Bank Sta=8025.79,15485.96
Exp/Cntr=0.3,0.1

Type RM Length L Ch R = 1 ,38153.91,1989.344000,1989.344000,1989.344000
XS GIS Cut Line= 3
841639.950654923738791.207056969842222.484931464737014.312500378
843701.207277324732683.809427763
#Sta/Elev= 30
8788.652 74.10249089.847 71.69129521.31861.034359889.64759.382959910.69455.29392
9942.26559.3943610015.9350.4991510088.87 67.6877 10447.4 57.200510573.6961.54319
10657.8857.6855111841.3756.17741 11862.5 51.594411883.6457.3779212401.4257.23326
12475.3864.6846712496.5261.9347412528.2248.2888112581.0559.5369113151.6755.44916
13225.6448.2104713265.8254.6029713796.2557.0667114662.7474.8051814852.9485.74351
14874.0894.4457614937.4894.5485915011.45104.459915085.41106.041515234.61126.5945
#Mann= 3 , 0 , 0
8788.652    0.04       08788.652    0.04       015234.61    0.04       0
#XS Ineff= 2 , 0
       09931.596        13934.43       0
Bank Sta=8788.652,15234.61
Exp/Cntr=0.3,0.1

Type RM Length L Ch R = 1 ,36164.57,1362.803000,1362.803000,1362.803000
XS GIS Cut Line= 6
842469.541668137738938.835748619842855.945146405737974.538117217
 842966.10164371737834.872285951843460.295747517737391.321732265
843564.096018032737186.483352532844259.901495292732213.592052802
#Sta/Elev= 30
8396.677130.67188474.884108.29228538.546105.82248687.23876.551878911.46762.44366
9688.39352.910439916.25357.47975    999947.5499910035.9957.5563410874.6856.64671
11026.1450.3811511329.0655.9012711598.68 52.136211631.9846.6670211652.1854.29273
11773.3557.8399611833.9344.2483711874.3255.2728113328.3555.7932913378.8453.91917
13409.1345.8471913439.4255.6615713954.39 56.453314196.7368.4684414469.3673.45833
14499.6578.9610815055.0192.3196615145.88107.599915448.81127.305615531.01139.0148
#Mann= 3 , 0 , 0
8396.677  0.0407       08396.677  0.0407       015531.01  0.0407       0
#XS Ineff= 2 , 0
       09180.139        13596.41       0
Bank Sta=8396.677,15531.01
Exp/Cntr=0.3,0.1

Type RM Length L Ch R = 1 ,34801.76,1229.199600,1229.199600,1229.199600
XS GIS Cut Line= 3
843792.664454045739931.011340555843870.566849835738243.872260266
844632.409421349731886.437305911
#Sta/Elev= 30
8686.587107.54938972.903103.96859022.95682.666869170.82570.948119513.47855.47446
9943.93755.940319983.97944.5721610064.0656.3886911703.8351.7987711764.2660.49256
12016.0549.7557912469.2753.9085212499.4842.3349912559.9154.3944914201.5855.03642
   14262 46.633214342.5853.9358615661.9572.5620515883.5285.8393415903.6794.64885
16145.38114.956416215.88112.061816296.4693.81785 16387.194.7321916487.82106.7214
16507.96129.297716538.17136.464416638.89113.067316679.18129.252916778.44143.4322
#Mann= 3 , 0 , 0
8686.587    0.04       08686.587    0.04       016778.44    0.04       0
#XS Ineff= 2 , 0
       09777.638        14409.86       0
Bank Sta=8686.587,16778.44
Exp/Cntr=0.3,0.1

Type RM Length L Ch R = 1 ,33572.56,1447.798100,1447.798100,1447.798100
XS GIS Cut Line= 2
844472.816479787741031.818360554844859.374581493731776.733258636
#Sta/Elev= 30
6939.294192.43786996.162170.48567256.38997.30016 7486.5961.619117856.91253.23495
8317.31351.372949958.74354.800439998.77842.6502810038.8151.3530710889.5554.41916
11540.1247.8859811650.22 55.550411690.2540.2069511740.29 50.032111810.3651.23407
13401.7455.4831713451.7943.4567813481.8151.1014313661.97 53.583813912.1949.37387
14372.5956.0076714432.6449.9258514532.73 59.073314893.0464.3579415243.3581.84722
15383.4779.1089815723.7793.1604615753.7983.9349715823.8577.2119116202.45152.0882
#Mann= 3 , 0 , 0
6939.294    0.04       06939.294    0.04       016202.45    0.04       0
#XS Ineff= 2 , 0
       08659.378         13617.3       0
Bank Sta=6939.294,16202.45
Exp/Cntr=0.3,0.1

Type RM Length L Ch R = 1 ,32124.77,1549.327600,1549.327600,1549.327600
XS GIS Cut Line= 6
844595.129528617740986.230980128845434.767543609739018.602689605
845647.652186265738500.643955509845689.892663711738177.632000769
845722.765858081735457.498510617845821.074571046731559.823668527
#Sta/Elev= 30
  7613.9163.9803 7713.09131.42047876.17698.64497 8199.5859.39161 8343.6954.31157
9474.42247.893189940.88252.3779110005.75 42.291110059.8159.2642510200.9949.88884
11511.6546.4875912511.7253.9706812561.7239.2166112621.7350.7698112981.7545.17039
 13731.954.4427313851.9448.4374214122.0256.3650614232.0651.9306715462.4564.49516
15642.5164.6500515692.5256.2737515742.5470.4444616402.7577.0198716432.7684.49965
 16872.9 97.649116932.92110.648617032.95149.378817062.96152.9792 17258.2228.7558
#Mann= 3 , 0 , 0
  7613.9  0.0395       0  7613.9  0.0395       0 17258.2  0.0395       0
#XS Ineff= 2 , 0
       09111.861        13814.34       0
Bank Sta=7613.9,17258.2
Exp/Cntr=0.3,0.1

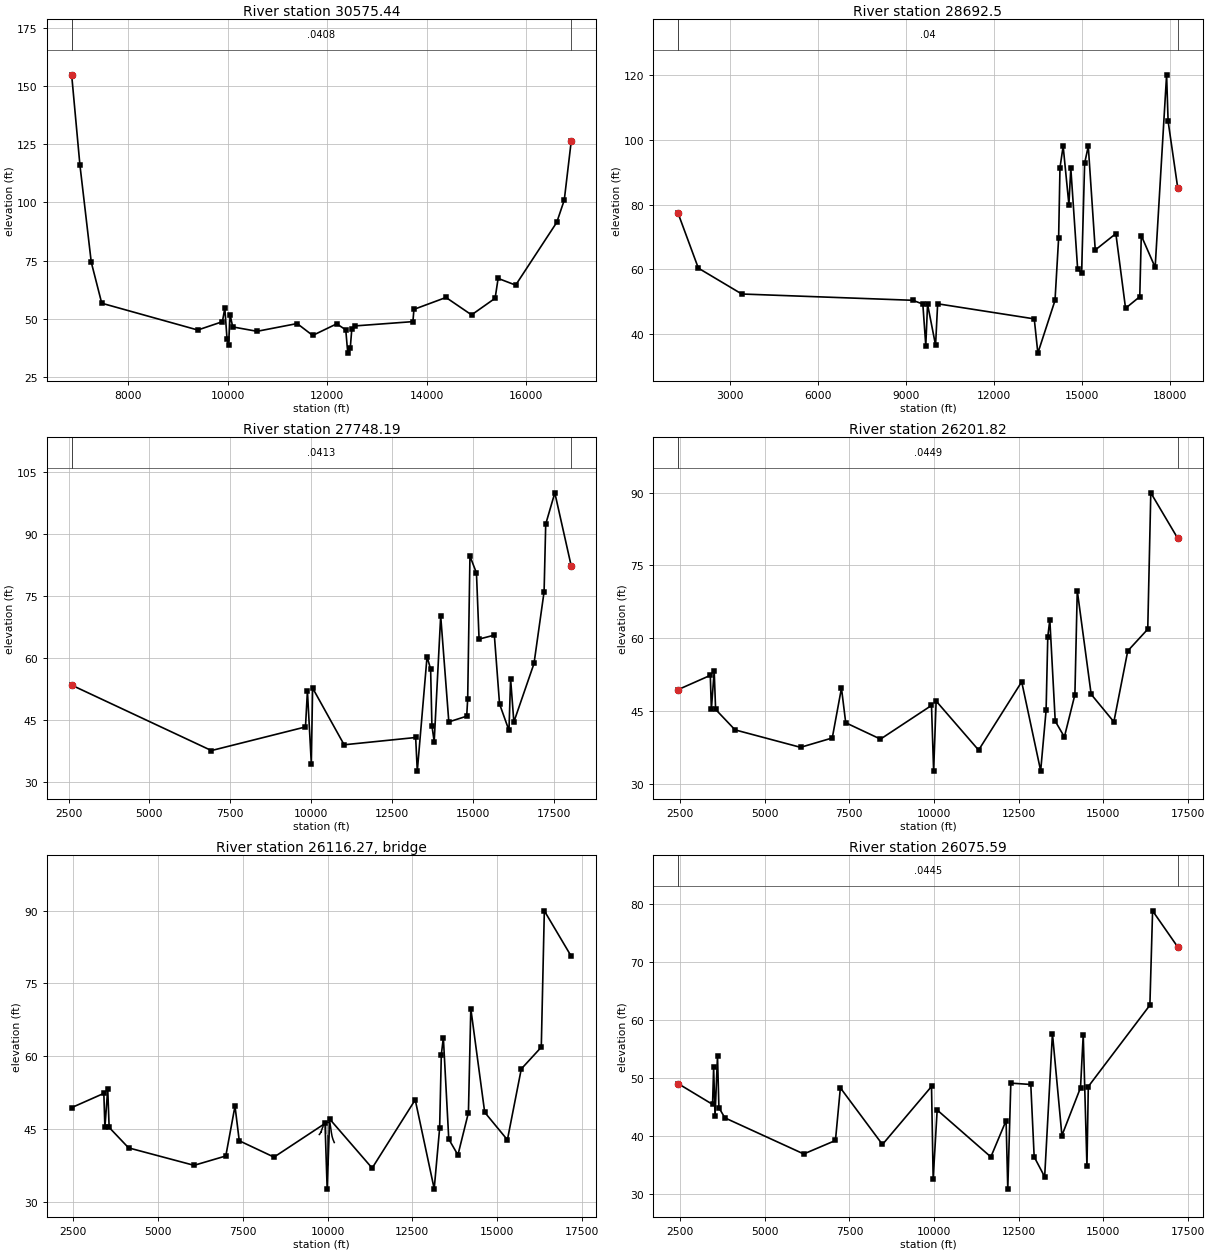
Type RM Length L Ch R = 1 ,30575.44,1882.935600,1882.935600,1882.935600
XS GIS Cut Line= 5
844718.691199431740954.042654322846539.601286932739367.619225156
846773.813510119739001.260175497 846929.89856838738432.260505224
847766.129555442731874.865754976
#Sta/Elev= 30
6857.409154.91237023.407116.18877251.75574.317227462.60556.652659394.25445.12841
9890.054 48.70689938.57554.565449983.37941.0605710014.1838.82654 10045.651.57573
10097.4446.4572610586.8944.5712111393.3747.9028811705.8842.7956712189.7747.79082
12371.2245.1959812411.5535.1832212461.9537.40422 12492.245.4322312562.76 46.8986
13722.0848.7379513742.2454.0145214387.4259.1288214901.55 51.637315375.3658.78494
15435.8467.3281315788.6864.4440916615.3291.4347716766.53101.0411 16907.8126.6246
#Mann= 3 , 0 , 0
6857.409  0.0408       06857.409  0.0408       0 16907.8  0.0408       0
#XS Ineff= 2 , 0
       08643.242        12617.31       0
Bank Sta=6857.409,16907.8
Exp/Cntr=0.3,0.1

Type RM Length L Ch R = 1 , 28692.5,944.318000,944.318000,944.318000
XS GIS Cut Line= 6
 846316.97974783748197.463655122846789.887001948745418.767294794
847919.095119029740409.488960463848242.315985235 737343.82224598
848385.335903375736429.549424199849585.759683742731503.363456325
#Sta/Elev= 30
 1224.1977.285631913.85560.386253395.18652.402459223.96150.462599567.91149.30149
9668.78736.498829729.312  49.25610002.2636.6059410073.2249.3818413367.3244.72592
13489.9634.1623414074.6550.4115214197.9969.5916914244.6591.3978914352.4898.00625
14548.4280.0093914613.6291.21036 14847.6 59.968514981.9258.9774915085.2592.77108
15209.24  97.998 15446.9 65.969216149.5271.0321416480.1747.9999216964.7551.57015
17016.2270.4160817489.42 60.617317879.59120.019717930.81105.730318260.2985.07388
#Mann= 3 , 0 , 0
 1224.19    0.04       0 1224.19    0.04       018260.29    0.04       0
#XS Ineff= 2 , 0
       09789.291        13531.85       0
Bank Sta=1224.19,18260.29
Exp/Cntr=0.3,0.1

Type RM Length L Ch R = 1 ,27748.19,1546.369900,1546.369900,1546.369900
XS GIS Cut Line= 4
 847469.13752042  746734.4470798848920.290423183739826.500836816
848954.928477546739293.249659833849767.291712858731478.150491129
#Sta/Elev= 30
 2595.4753.367796917.23137.527129826.05543.247449886.18151.9675710006.4334.38666
10046.52 52.668411021.28  38.92713233.1340.69055 13283.432.5485313585.0260.24607
13695.6157.2578413735.8343.56177 13806.239.6694914007.2870.1131114258.6344.46685
14811.5945.8528314841.7550.0817614912.1384.5990515113.21 80.525815193.6464.51353
15666.1765.4746415827.0348.81812 16118.642.4060616168.8754.8915916269.4144.44223
16892.7558.6072817204.4275.9760617254.6992.3417517536.1999.9243218045.7782.13167
#Mann= 3 , 0 , 0
 2595.47  0.0413       0 2595.47  0.0413       018045.77  0.0413       0
#XS Ineff= 2 , 0
       09891.294        13358.62       0
Bank Sta=2595.47,18045.77
Exp/Cntr=0.3,0.1

Type RM Length L Ch R = 1 ,26201.82,126.227700,126.227700,126.227700
XS GIS Cut Line= 6
847702.342128544745895.397455028849012.467041178741360.763752804
849522.511028568739868.982272494849973.949005638738303.877615584
850003.955386329737261.844305759849925.157899508731489.238165845
#Sta/Elev= 30
2448.038 49.44513398.05652.377283429.36245.355063512.84453.285793554.58545.37274
4128.52141.162926060.74337.570556997.23739.495347268.71849.753397394.35442.62715
8420.13339.261719925.64146.186949988.873 32.675310062.6847.0982511316.3637.00021
12587.67 51.0539 13147.7 32.740713307.7145.1710813357.7160.3164313417.7163.83962
13577.7242.9563613847.7339.7062114157.7548.4036214227.7569.8195214637.7748.48289
 15307.842.8143115717.8257.4050116307.8561.8775116397.8589.9330517193.6580.56273
#Mann= 3 , 0 , 0
2448.038  0.0449       02448.038  0.0449       017193.65  0.0449       0
#XS Ineff= 2 , 0
       09931.211        12081.17       0
Bank Sta=2448.038,17193.65
Exp/Cntr=0.3,0.1

Type RM Length L Ch R = 3 ,26116.27,,,
BEGIN DESCRIPTION:
END DESCRIPTION:
Bridge Culvert--1,0,-1,-1, 0
Deck Dist Width WeirC Skew NumUp NumDn MinLoCord MaxHiCord MaxSubmerge Is_Ogee
47.613850,31.000000,2.6,0, 48, 48, , , 0.95, 0, 0,0,,
 9756.87 9758.11 9761.73 9768.86 9779.60 9789.06 9790.35 9801.09 9811.84 9816.39
 9822.58 9833.33 9843.71 9844.08 9854.82 9865.57 9871.04 9876.31 9887.06 9897.80
 9898.37 9908.55 9919.29 9925.69 9930.04 9937.55 9948.49 9948.4910046.4910046.49
10071.2510080.4710089.6510091.0810091.2110101.5910111.9810122.3610126.3710132.74
10143.1210153.5010163.6110163.8810174.2610184.6510195.0310198.32
   43.92   43.95   43.97   43.98   44.10   44.23   44.24   44.40   44.36   44.53
   44.80   44.91   45.21   45.22   45.34   45.57   45.69   45.76   46.03   46.12
   46.13   46.34   46.49   46.48   46.50   46.57   46.55   46.55   46.34   46.34
   46.29   45.86   45.46   45.39   45.38   44.91   44.38   43.97   43.81   43.57
   43.30   43.06   42.85   42.84   42.67   42.51   42.30   42.26
 -956.08 -956.05 -956.03 -956.02 -955.90 -955.77 -955.76 -955.60 -955.64 -955.47
 -955.20 -955.09 -954.79 -954.78 -954.66 -954.43 -954.31 -954.24 -953.97 -953.88
 -953.87 -953.66 -953.51 -953.52 -953.50 -953.43 -953.45   44.05   43.84 -953.66
 -953.71 -954.14 -954.54 -954.61 -954.62 -955.09 -955.62 -956.03 -956.19 -956.43
 -956.70 -956.94 -957.15 -957.16 -957.33 -957.49 -957.70 -957.74
 9756.87 9758.11 9761.73 9768.86 9779.60 9789.06 9790.35 9801.09 9811.84 9816.39
 9822.58 9833.33 9843.71 9844.08 9854.82 9865.57 9871.04 9876.31 9887.06 9897.80
 9898.37 9908.55 9919.29 9925.69 9930.04 9937.55 9951.79 9951.7910049.7910049.79
10071.2510080.4710089.6510091.0810091.2110101.5910111.9810122.3610126.3710132.74
10143.1210153.5010163.6110163.8810174.2610184.6510195.0310198.32
   43.92   43.95   43.97   43.98   44.10   44.23   44.24   44.40   44.36   44.53
   44.80   44.91   45.21   45.22   45.34   45.57   45.69   45.76   46.03   46.12
   46.13   46.34   46.49   46.48   46.50   46.57   46.54   46.54   46.33   46.33
   46.29   45.86   45.46   45.39   45.38   44.91   44.38   43.97   43.81   43.57
   43.30   43.06   42.85   42.84   42.67   42.51   42.30   42.26
 -956.08 -956.05 -956.03 -956.02 -955.90 -955.77 -955.76 -955.60 -955.64 -955.47
 -955.20 -955.09 -954.79 -954.78 -954.66 -954.43 -954.31 -954.24 -953.97 -953.88
 -953.87 -953.66 -953.51 -953.52 -953.50 -953.43 -953.46   44.04   43.83 -953.67
 -953.71 -954.14 -954.54 -954.61 -954.62 -955.09 -955.62 -956.03 -956.19 -956.43
 -956.70 -956.94 -957.15 -957.16 -957.33 -957.49 -957.70 -957.74
Pier Skew, UpSta & Num, DnSta & Num=  ,9980.66, 2 ,9983.95, 2 , 0 , 0 , 0 ,,
    3.00    3.00
 -953.52   46.48
    3.00    3.00
 -953.53   46.47
Pier Skew, UpSta & Num, DnSta & Num=  ,10014.33, 2 ,10017.62, 2 , 0 , 0 , 0 ,,
    3.00    3.00
 -953.59   46.41
    3.00    3.00
 -953.60   46.40
BR Coef=-1 , 0 , 0 ,, 0 ,,,0.8,0,1,0,
WSPro=,,,, 1 ,,,, 0 ,,,, 0 ,,,,-1 ,-1 ,-1 , 0 , 0 , 0 , 0 , 0
BC Design=,, 0 ,, 0 ,,,,,,

Type RM Length L Ch R = 1 ,26075.59,950.872600,950.872600,950.872600
XS GIS Cut Line= 6
847802.240067073 745963.72242122849386.657529238740459.727698693
850054.956047074738473.570750632850120.164106796737394.311369221
850128.960456685736946.302339701850131.443676936731530.899373451
#Sta/Elev= 30
2435.10749.044973453.57445.471763484.79251.840783526.41743.395723599.25953.78421
3640.88444.899213817.78743.156576148.75236.95148  7085.339.268587230.98548.31468
8474.33138.579469924.75648.552439973.80332.65856 10091.644.5090611678.9136.44125
12128.9342.6895212178.9330.9072212268.9349.1281512858.9348.8940812958.93  36.458
13268.9333.0232113498.9357.6475213778.9340.1207114328.9348.3446514408.9357.45586
14518.9334.8249214558.9348.5358616378.9362.5263216458.93 78.742417203.0372.52042
#Mann= 3 , 0 , 0
2435.107  0.0445       02435.107  0.0445       017203.03  0.0445       0
#XS Ineff= 2 , 0
       09922.608        12084.38       0
Bank Sta=2435.107,17203.03
Exp/Cntr=0.3,0.1

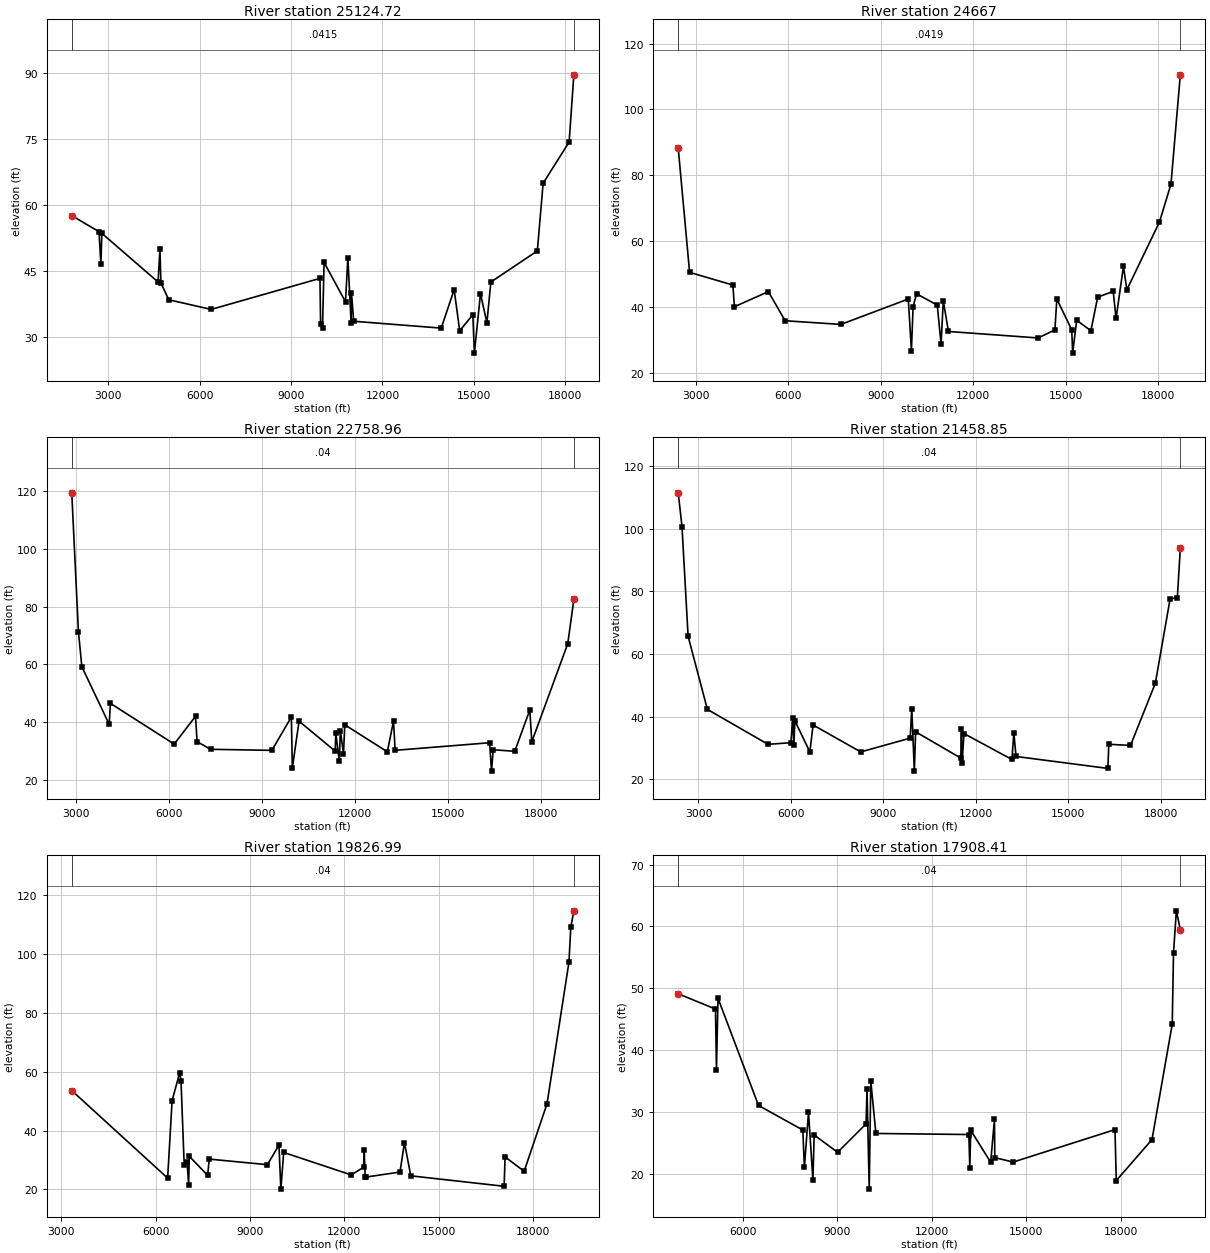
Type RM Length L Ch R = 1 ,25124.72,457.711500,457.711500,457.711500
XS GIS Cut Line= 6
 847988.72710435747492.241790186 849927.96098164 739659.70969245
850476.145463785739444.678566158850806.097609257739226.916246204
851780.490798366735832.423596887852073.119285918731959.996101641
#Sta/Elev= 30
1806.29757.624332700.25653.977142762.10546.578462793.02953.603274638.17442.55735
4700.02250.127244730.94642.364364988.64838.527926380.23836.334979950.224 43.3738
9971.721 33.003310034.5732.1766310086.5146.9988310788.93 38.066410866.6748.04144
10973.4733.2799810983.95  40.14811057.3133.64869 13929.632.0921114354.6440.80532
 14536.6 31.486314967.8235.1390515017.9726.4154215218.5439.8997115429.1433.30718
15559.5142.5587717083.84 49.610817274.3864.9693718126.8174.3112618282.2589.57573
#Mann= 3 , 0 , 0
1806.297  0.0415       01806.297  0.0415       018282.25  0.0415       0
#XS Ineff= 2 , 0
       09896.283        14336.43       0
Bank Sta=1806.297,18282.25
Exp/Cntr=0.3,0.1

Type RM Length L Ch R = 1 ,   24667,1908.047900,1908.047900,1908.047900
XS GIS Cut Line= 6
849046.799065744747449.825191211849980.962616634740666.058762011
850141.365170394740042.938953674 850913.00255449739313.369424675
852019.876453663735710.344306582852403.506427685731784.356706997
#Sta/Elev= 30
2437.46388.132482805.73150.459964208.84846.59457 4259.3240.008255359.60644.59725
5904.70235.743917711.59434.634589896.52742.352939998.44526.6638810052.8639.97055
10164.3643.9362110836.6540.5020110960.0228.6344811031.5241.8369111198.9432.48736
14106.4830.5165514651.1132.9719514713.8742.3568515197.0732.9583215227.1225.90592
15357.3335.8768515818.0632.7268516038.4242.9226316541.3344.6631216633.97  36.451
16873.7152.25786 16984.545.1743718042.0565.7681818414.7177.2795118717.51110.4923
#Mann= 3 , 0 , 0
2437.463  0.0419       02437.463  0.0419       018717.51  0.0419       0
#XS Ineff= 2 , 0
       09793.508        14724.03       0
Bank Sta=2437.463,18717.51
Exp/Cntr=0.3,0.1

Type RM Length L Ch R = 1 ,22758.96,1300.106500,1300.106500,1300.106500
XS GIS Cut Line= 4
850191.938480009747726.291423826851339.765857619740850.013207601
852129.364360508737775.373666094854004.833327708732008.203680523
#Sta/Elev= 30
2858.174119.28343072.38971.370933183.91159.224624065.94839.324554106.502 46.5519
 6164.59 32.50196853.998  42.091 6904.6933.34536 7340.6430.702169317.62130.33563
 9948.3441.845749979.31324.2417610196.1340.41781 11362.830.0706811383.4436.21518
11497.0126.5536211527.99 37.129711631.2329.2352611672.5339.1718813046.4629.84257
13246.2540.4442313298.8330.3486916348.3232.9642316411.4123.1626216463.9930.53211
17161.1930.0232617646.2344.29613 17710.9 33.299318872.0467.1905919068.46 82.4588
#Mann= 3 , 0 , 0
2858.174    0.04       02858.174    0.04       019068.46    0.04       0
#XS Ineff= 2 , 0
       08565.634        15378.34       0
Bank Sta=2858.174,19068.46
Exp/Cntr=0.3,0.1

Type RM Length L Ch R = 1 ,21458.85,1631.861200,1631.861200,1631.861200
XS GIS Cut Line= 5
850444.838398003747893.339940663852348.230699833740957.870311474
852523.755907716740256.854656692853101.374304892737673.889670153
854231.721627462732060.883875706
#Sta/Elev= 30
2343.434111.46172466.149100.57022663.17565.648863288.66242.297975255.61531.13439
6002.23731.658486054.08639.699716095.56531.011516126.67438.648056613.71828.71898
6717.75137.320048262.84528.702539868.186 33.1171 9919.7342.57152 10002.222.57317
10043.4335.1406511510.0426.7376711530.5335.9130511551.0325.1600311612.5134.56721
13168.8526.2940913230.0634.8146113301.4627.2547616280.0823.4406216310.69 31.1563
17014.5430.77277 17820.450.6474718299.8377.6122718534.4577.9794718630.4693.77525
#Mann= 3 , 0 , 0
2343.434    0.04       02343.434    0.04       018630.46    0.04       0
#XS Ineff= 2 , 0
       07576.843         15230.4       0
Bank Sta=2343.434,18630.46
Exp/Cntr=0.3,0.1

Type RM Length L Ch R = 1 ,19826.99,1918.581900,1918.581900,1918.581900
XS GIS Cut Line= 4
852574.107325313748010.639931905853153.035982155744205.884114347
 854115.38297269736700.959137981854773.009747492732190.044826051
#Sta/Elev= 30
3331.765  53.5956382.115 23.82756523.72650.166746766.48859.717526806.94956.99169
  6908.128.425796999.13629.405827049.71121.609597069.94131.257297655.05324.76718
7705.46230.28767 9554.4828.392369923.47535.054999983.96720.07883 10074.732.55279
12222.1424.9151612615.3427.52519 12635.533.3996412665.7524.2847212706.0724.19976
13774.75 25.8921 13915.935.8907914117.5424.6002617087.1321.0453417117.4431.02778
17723.7926.15903 18451.449.0767919148.6997.1956619209.33109.209719305.29114.7222
#Mann= 3 , 0 , 0
3331.765    0.04       03331.765    0.04       019305.29    0.04       0
#XS Ineff= 2 , 0
       07243.053        16204.37       0
Bank Sta=3331.765,19305.29
Exp/Cntr=0.3,0.1

Type RM Length L Ch R = 1 ,17908.41,1594.867700,1594.867700,1594.867700
XS GIS Cut Line= 2
853775.906769761748753.028704568855088.449838864732879.819269135
#Sta/Elev= 30
 3957.3749.106435139.41946.632845169.52136.856365219.69248.37183 6504.0631.05299
7908.83827.086337959.00921.039668089.45329.920028229.93119.030548270.06726.28394
9012.59323.481129915.66428.071749945.767 33.658910016.0117.5297510066.1834.99179
10226.7226.5269813176.7626.3549613206.8620.9755413236.9627.0338713869.1121.87329
13989.5228.8421413999.5522.6194314581.5321.9047717812.5227.1473217852.6618.90695
18986.52 25.5385 19628.744.1916819668.8455.6975819759.1562.5137919884.7559.47629
#Mann= 3 , 0 , 0
 3957.37    0.04       0 3957.37    0.04       019884.75    0.04       0
#XS Ineff= 2 , 0
       08231.403        17600.01       0
Bank Sta=3957.37,19884.75
Exp/Cntr=0.3,0.1

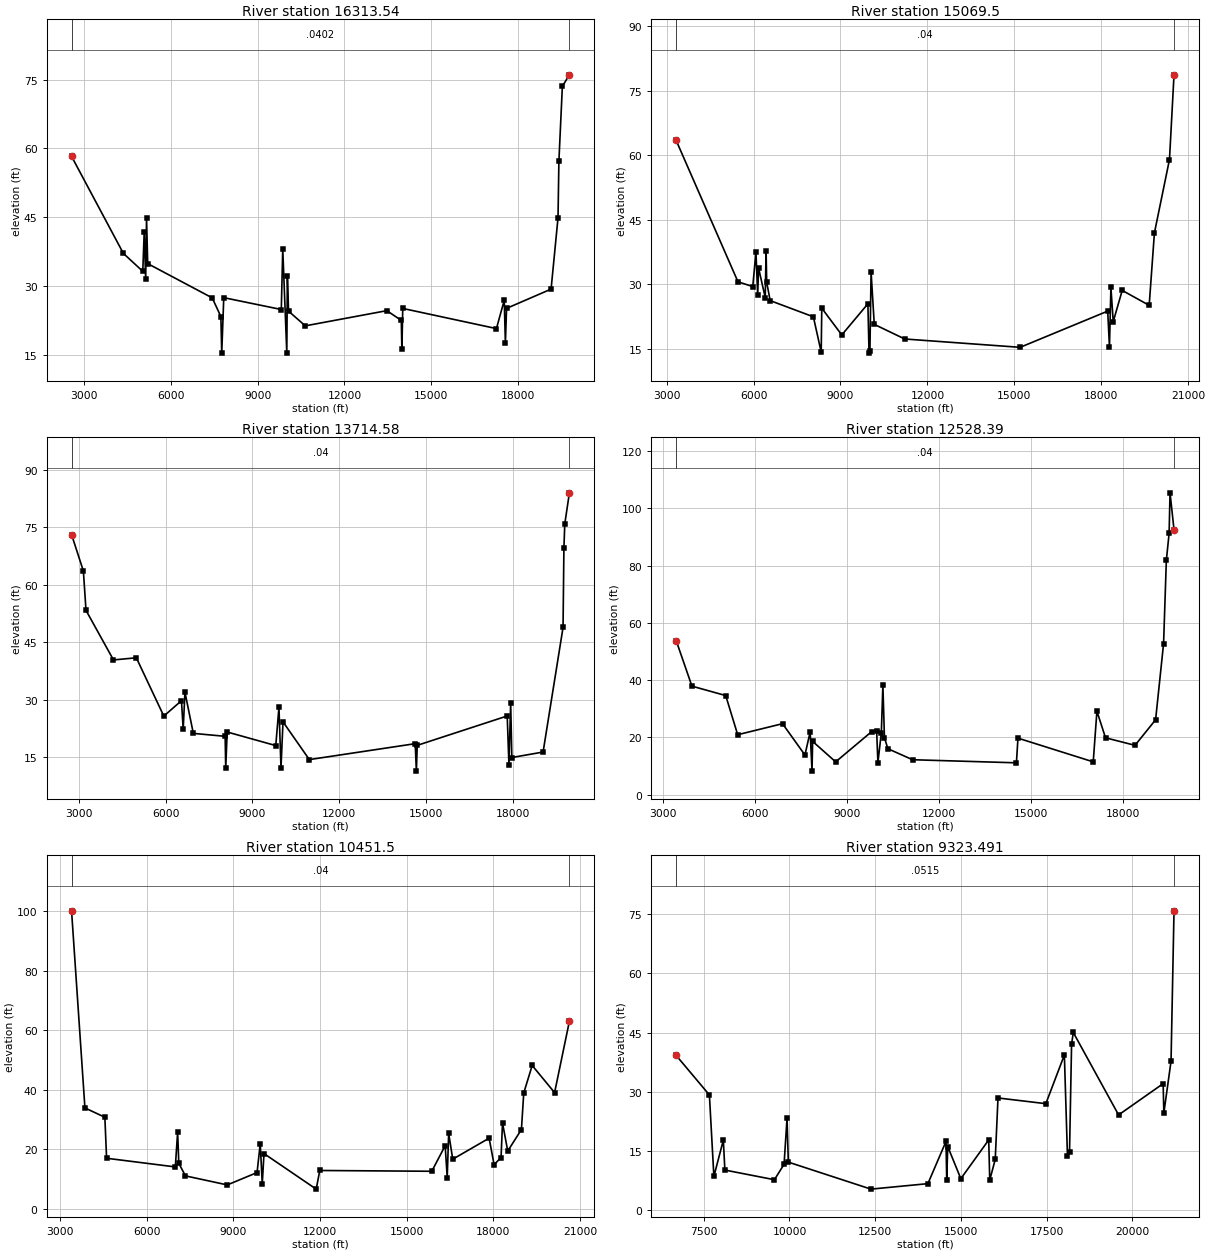
Type RM Length L Ch R = 1 ,16313.54,1244.042000,1244.042000,1244.042000
XS GIS Cut Line= 6
855533.141818293750047.382289767855497.466996509749156.485342873
855475.406660507747903.831439519855486.375524827746634.138122779
855529.837147604745330.401846773855385.829233827732831.511900717
#Sta/Elev= 30
2560.11458.284484353.43437.152195023.44733.267795073.44841.906395123.44931.50353
5153.44944.80419 5193.4534.940877424.28327.485737724.30323.418427754.30515.45596
7824.30927.531329814.44124.952139864.44538.1396510004.4515.4883710024.4632.27353
10064.4624.59433 10644.521.3948413464.6824.7017413964.7222.5808313984.7216.25726
14014.7225.1847917254.9420.7960817524.95 26.970217564.9617.6387917604.9625.19817
19145.0629.3911919385.08 44.928619415.0857.2194119535.09 73.531819778.59 76.0367
#Mann= 3 , 0 , 0
2560.114  0.0402       02560.114  0.0402       019778.59  0.0402       0
#XS Ineff= 2 , 0
       07830.264        17543.72       0
Bank Sta=2560.114,19778.59
Exp/Cntr=0.3,0.1

Type RM Length L Ch R = 1 , 15069.5,1354.917400,1354.917400,1354.917400
XS GIS Cut Line= 2
856750.870127463749795.913583338856146.050261879732628.738486626
#Sta/Elev= 30
3331.433 63.39535463.66930.551715973.98529.441116084.05337.452786144.09127.39957
6174.10933.763136404.25226.895756434.27137.742586454.28330.458946574.35726.17972
8065.28222.415498335.44914.215878355.46224.42066 9045.8918.197149946.44825.43775
9986.47313.9752610016.4914.4036510056.5232.8254910166.58 20.658311217.2417.26031
15199.7115.3221818221.5823.7388918281.6215.4462718331.6529.23603 18411.721.28633
18721.89 28.550319652.4725.0751819832.5841.89112 20352.958.9665320509.26 78.6422
#Mann= 3 , 0 , 0
3331.433    0.04       03331.433    0.04       020509.26    0.04       0
#XS Ineff= 2 , 0
       08378.356        18214.71       0
Bank Sta=3331.433,20509.26
Exp/Cntr=0.3,0.1

Type RM Length L Ch R = 1 ,13714.58,1186.188900,1186.188900,1186.188900
XS GIS Cut Line= 2
  857995.6710801750083.962283239857257.679257391732875.233097779
#Sta/Elev= 30
2741.95373.086573151.29163.567013241.37453.328994192.24740.407024982.97340.96793
5933.84625.774166544.40729.785766604.46222.300226664.51732.019156954.78421.26818
8055.79520.503578075.81312.165068125.85921.626079807.40318.088959917.50428.05773
9987.56812.3071510057.6324.2715410968.47 14.437314631.8318.5863514671.8711.43119
 14701.918.1502817814.7625.8056317874.8113.0592217934.8729.22877 17974.914.97948
 19055.916.4047819746.5348.8710219776.5669.5341219806.5975.86337 19966.583.95464
#Mann= 3 , 0 , 0
2741.953    0.04       02741.953    0.04       0 19966.5    0.04       0
#XS Ineff= 2 , 0
       08135.059        17715.01       0
Bank Sta=2741.953,19966.5
Exp/Cntr=0.3,0.1

Type RM Length L Ch R = 1 ,12528.39,2076.886600,2076.886600,2076.886600
XS GIS Cut Line= 4
859071.913658735749078.269311642858662.137090141 742971.38097832
858467.526034879 741867.99318663857802.565085328732885.492580092
#Sta/Elev= 30
3416.94553.823673931.369 37.91285033.84234.621935424.71920.946876888.00324.80083
7619.64413.858197790.02621.968787850.1618.2293597870.20618.625158621.89311.46397
9797.90522.030819960.374 22.187110000.99 11.221410112.6921.6152610163.4638.30868
10214.2319.9079210325.9316.0608711132.2712.2100614521.5211.1341914571.6619.75272
17028.3611.4690417148.6929.1597117429.4619.8732518392.08 17.238419063.9226.16596
19324.6352.7895519414.8781.8748119505.1291.28676 19535.2105.434719665.0792.53026
#Mann= 3 , 0 , 0
3416.945    0.04       03416.945    0.04       019665.07    0.04       0
#XS Ineff= 2 , 0
       07877.146        16949.53       0
Bank Sta=3416.945,19665.07
Exp/Cntr=0.3,0.1

Type RM Length L Ch R = 1 , 10451.5,1128.012300,1128.012300,1128.012300
XS GIS Cut Line= 6
860149.775149814748607.836871311860245.165703574742558.502863148
860247.707767137741689.473622063860022.151794417741233.359115926
859019.809946412739728.571557687858033.722297125731786.156846155
#Sta/Elev= 30
3396.966100.2022 3859.86 33.92444549.94630.790864609.95317.002276990.24914.08872
7070.25925.827687110.26415.310147340.29311.076078790.4738.0365949820.556 12.1916
9930.55721.8743110000.568.44923210060.5618.5746611868.296.62135711992.2812.88974
15871.2312.6250216334.76 21.239616405.2910.5096316455.6825.3861116596.7516.68467
17856.3523.7525918028.79 14.8396 18269.517.2560818319.8828.8763418501.2619.44095
18974.8726.6567119055.4938.9444319347.7148.2023820123.63 39.072920636.38 63.0727
#Mann= 3 , 0 , 0
3396.966    0.04       03396.966    0.04       020636.38    0.04       0
#XS Ineff= 2 , 0
       07496.357        16203.94       0
Bank Sta=3396.966,20636.38
Exp/Cntr=0.3,0.1

Type RM Length L Ch R = 1 ,9323.491,115.502100,115.502100,115.502100
XS GIS Cut Line= 6
862714.167364104745429.370852296860240.861523855740601.740806591
 859717.87277153739187.087184243 859552.26413044738310.200252104
859270.047280187735263.163343664859298.690025274731628.005449305
#Sta/Elev= 30
6694.78939.228847664.27729.220867794.9158.5935798070.573 17.78048115.73410.20642
9560.5847.7595249842.74111.662549929.11123.30802 9966.8912.21428 12377.75.376389
14039.226.76193514567.8317.4718814587.937.73645514618.0716.1570314999.928.020998
15813.4317.8343315843.537.68264816004.0812.8938116084.3628.4635917480.2627.01596
18020.8839.3527718111.0713.7758918171.19  14.73318231.3142.1012318281.4145.04346
19602.88 24.168620902.9532.0890720922.9524.6250121132.9637.7711821219.9675.85512
#Mann= 3 , 0 , 0
6694.789  0.0515       06694.789  0.0515       021219.96  0.0515       0
#XS Ineff= 2 , 0
       08076.998        15812.75       0
Bank Sta=6694.789,21219.96
Exp/Cntr=0.3,0.1