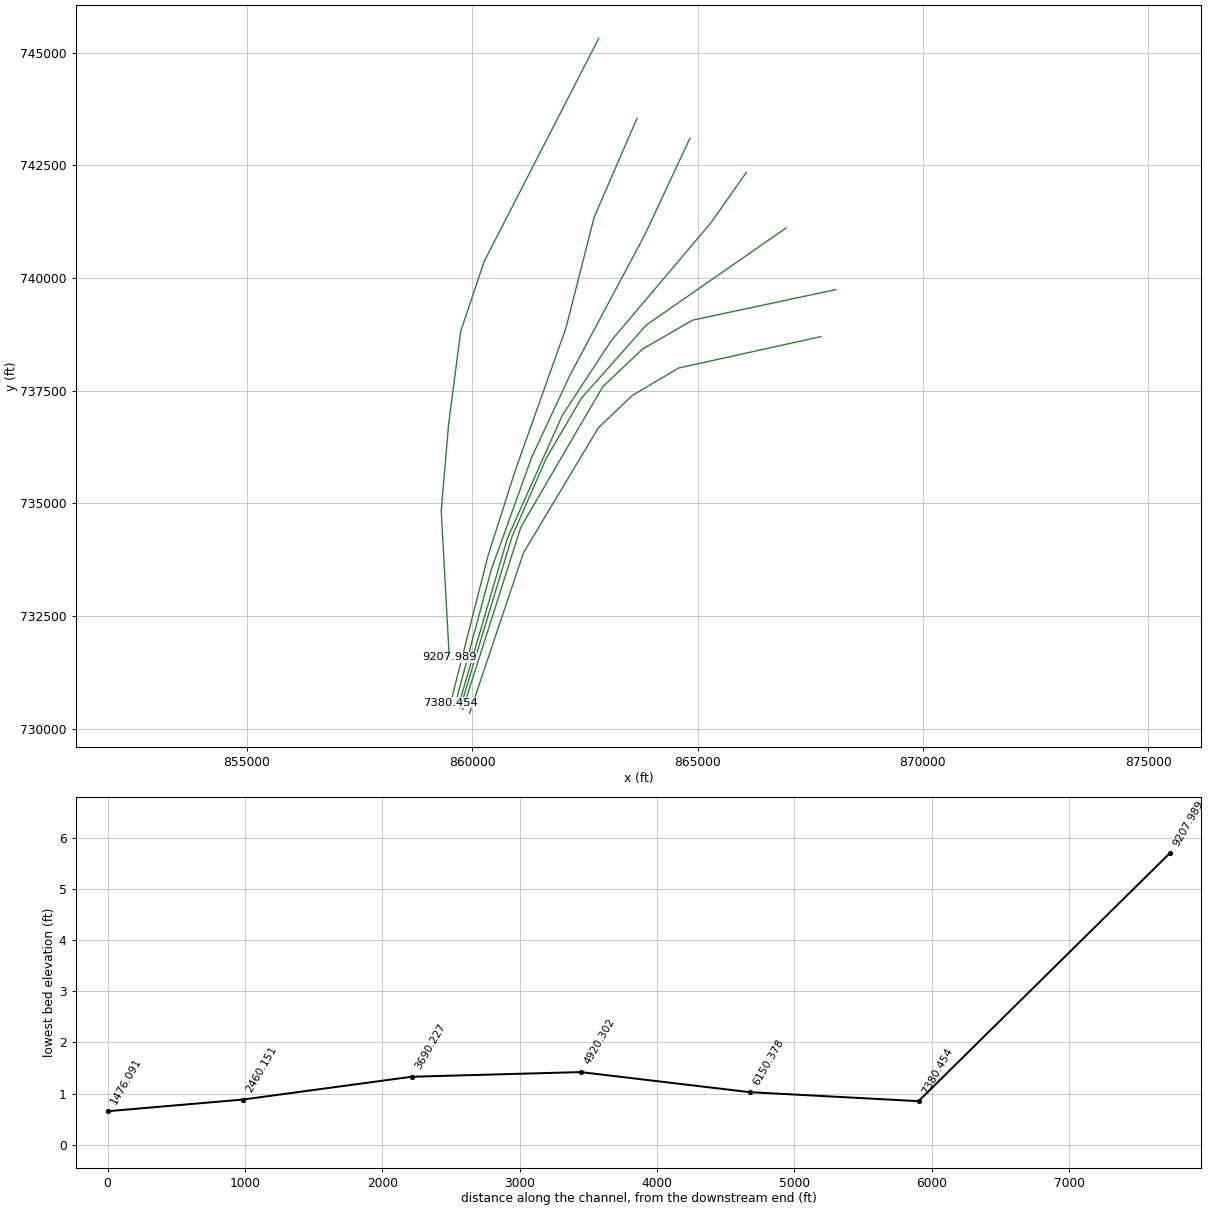
HEC-RAS study 8407_ras.prj: 8407

--- 8407_ras.g01 (geometry) --- (continued)

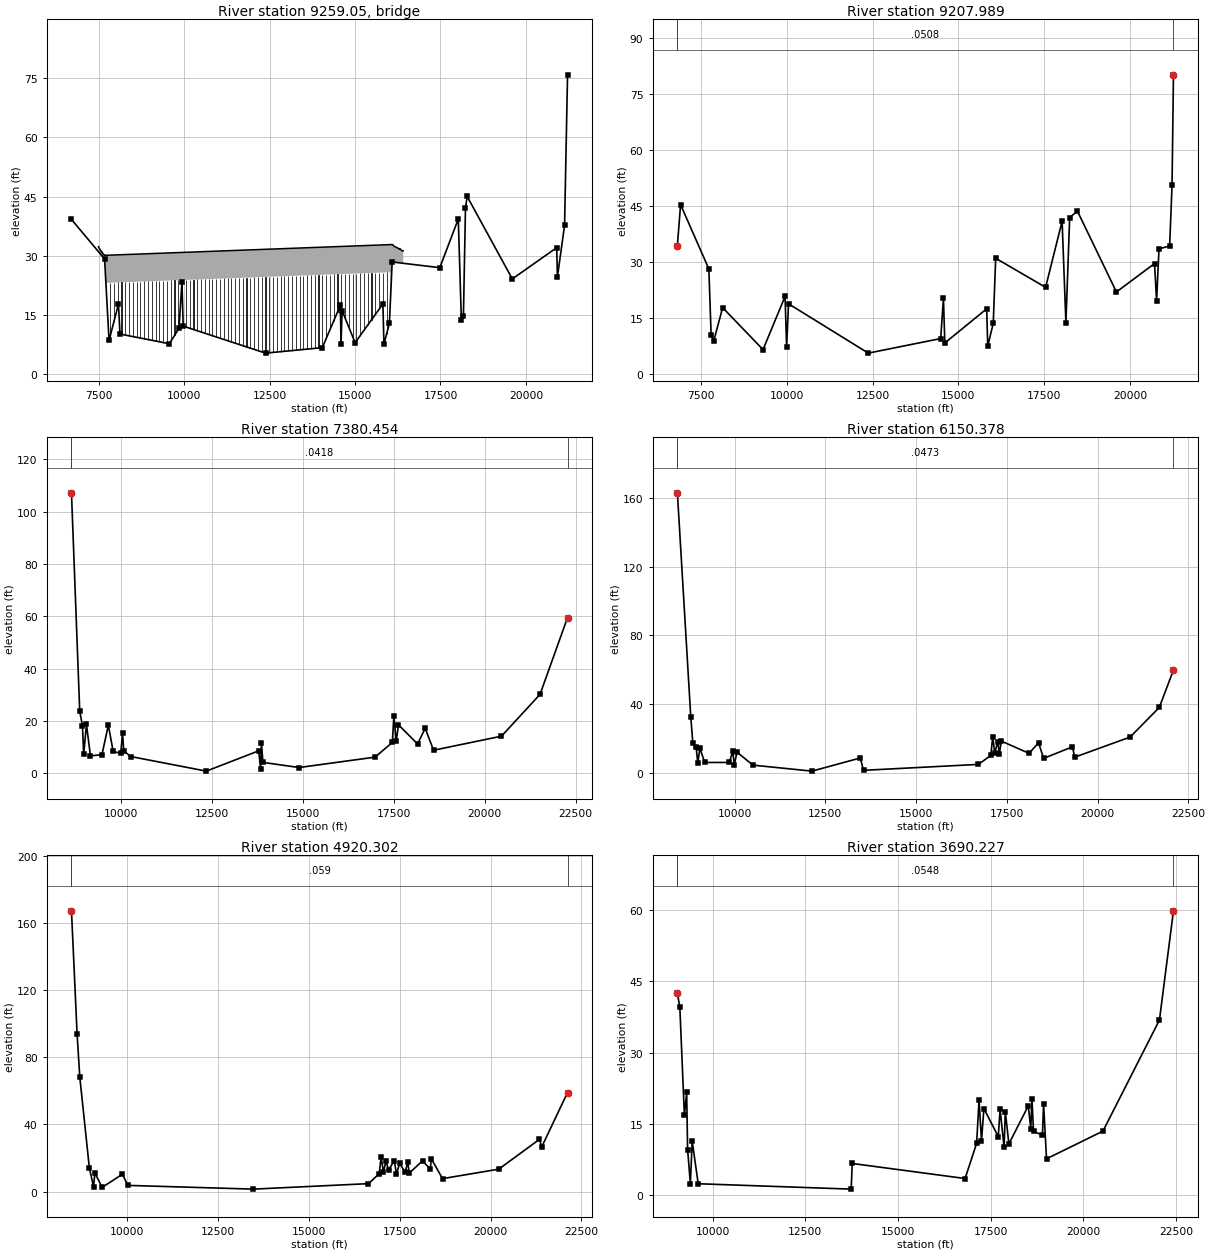
Type RM Length L Ch R = 3 , 9259.05,,,
BEGIN DESCRIPTION:
END DESCRIPTION:
Bridge Culvert--1,0,-1,-1, 0
Deck Dist Width WeirC Skew NumUp NumDn MinLoCord MaxHiCord MaxSubmerge Is_Ogee
27.251050,61.000000,2.6,0, 30, 30, , , 0.95, 0, 0,0,,
 7486.03 7492.66 7547.01 7560.09 7582.57 7593.81 7605.05 7616.28 7627.52 7650.00
 7661.24 7683.71 7717.27 7717.2716034.2716034.2716098.7816120.8016130.8416150.94
16201.1616221.2616241.3516291.5816301.6216311.6716321.7116331.7616381.9916407.78
   32.35   32.18   31.40   31.30   30.98   30.98   30.68   30.62   30.42   30.17
   30.25   30.13   30.16   30.16   32.86   32.86   32.88   32.59   32.59   32.35
   32.25   32.05   32.05   31.72   31.73   31.86   31.64   31.63   31.25   31.29
 -967.65 -967.82 -968.60 -968.70 -969.02 -969.02 -969.32 -969.38 -969.58 -969.83
 -969.75 -969.87 -969.84   23.16   25.86 -967.14 -967.12 -967.41 -967.41 -967.65
 -967.75 -967.95 -967.95 -968.28 -968.27 -968.14 -968.36 -968.37 -968.75 -968.71
 7486.03 7492.66 7547.01 7560.09 7582.57 7593.81 7605.05 7616.28 7627.52 7650.00
 7661.24 7683.71 7746.77 7746.7716063.7716063.7716098.7816120.8016130.8416150.94
16201.1616221.2616241.3516291.5816301.6216311.6716321.7116331.7616381.9916407.78
   32.35   32.18   31.40   31.30   30.98   30.98   30.68   30.62   30.42   30.17
   30.25   30.13   30.17   30.17   32.87   32.87   32.88   32.59   32.59   32.35
   32.25   32.05   32.05   31.72   31.73   31.86   31.64   31.63   31.25   31.29
 -967.65 -967.82 -968.60 -968.70 -969.02 -969.02 -969.32 -969.38 -969.58 -969.83
 -969.75 -969.87 -969.83   23.17   25.87 -967.13 -967.12 -967.41 -967.41 -967.65
 -967.75 -967.95 -967.95 -968.28 -968.27 -968.14 -968.36 -968.37 -968.75 -968.71
Pier Skew, UpSta & Num, DnSta & Num=  ,7826.22, 2 ,7855.72, 2 , 0 , 0 , 0 ,,
    4.00    4.00
 -969.81   30.19
    4.00    4.00
 -969.80   30.20
Pier Skew, UpSta & Num, DnSta & Num=  ,7937.16, 2 ,7966.66, 2 , 0 , 0 , 0 ,,
    4.00    4.00
 -969.77   30.23
    4.00    4.00
 -969.76   30.24
Pier Skew, UpSta & Num, DnSta & Num=  ,8048.11, 2 ,8077.61, 2 , 0 , 0 , 0 ,,
    4.00    4.00
 -969.73   30.27
    4.00    4.00
 -969.72   30.28
Pier Skew, UpSta & Num, DnSta & Num=  ,8159.06, 2 ,8188.56, 2 , 0 , 0 , 0 ,,
    4.00    4.00
 -969.70   30.30
    4.00    4.00
 -969.69   30.31
Pier Skew, UpSta & Num, DnSta & Num=  ,8270.00, 2 ,8299.50, 2 , 0 , 0 , 0 ,,
    4.00    4.00
 -969.66   30.34
    4.00    4.00
 -969.65   30.35
Pier Skew, UpSta & Num, DnSta & Num=  ,8380.95, 2 ,8410.45, 2 , 0 , 0 , 0 ,,
    4.00    4.00
 -969.63   30.37
    4.00    4.00
 -969.62   30.38
Pier Skew, UpSta & Num, DnSta & Num=  ,8491.90, 2 ,8521.40, 2 , 0 , 0 , 0 ,,
    4.00    4.00
 -969.59   30.41
    4.00    4.00
 -969.58   30.42
Pier Skew, UpSta & Num, DnSta & Num=  ,8602.84, 2 ,8632.34, 2 , 0 , 0 , 0 ,,
    4.00    4.00
 -969.55   30.45
    4.00    4.00
 -969.54   30.46
Pier Skew, UpSta & Num, DnSta & Num=  ,8713.79, 2 ,8743.29, 2 , 0 , 0 , 0 ,,
    4.00    4.00
 -969.52   30.48
    4.00    4.00
 -969.51   30.49
Pier Skew, UpSta & Num, DnSta & Num=  ,8824.74, 2 ,8854.24, 2 , 0 , 0 , 0 ,,
    4.00    4.00
 -969.48   30.52
    4.00    4.00
 -969.47   30.53
Pier Skew, UpSta & Num, DnSta & Num=  ,8935.68, 2 ,8965.18, 2 , 0 , 0 , 0 ,,
    4.00    4.00
 -969.44   30.56
    4.00    4.00
 -969.44   30.56
Pier Skew, UpSta & Num, DnSta & Num=  ,9046.63, 2 ,9076.13, 2 , 0 , 0 , 0 ,,
    4.00    4.00
 -969.41   30.59
    4.00    4.00
 -969.40   30.60
Pier Skew, UpSta & Num, DnSta & Num=  ,9157.58, 2 ,9187.08, 2 , 0 , 0 , 0 ,,
    4.00    4.00
 -969.37   30.63
    4.00    4.00
 -969.36   30.64
Pier Skew, UpSta & Num, DnSta & Num=  ,9268.52, 2 ,9298.02, 2 , 0 , 0 , 0 ,,
    4.00    4.00
 -969.34   30.66
    4.00    4.00
 -969.33   30.67
Pier Skew, UpSta & Num, DnSta & Num=  ,9379.47, 2 ,9408.97, 2 , 0 , 0 , 0 ,,
    4.00    4.00
 -969.30   30.70
    4.00    4.00
 -969.29   30.71
Pier Skew, UpSta & Num, DnSta & Num=  ,9490.42, 2 ,9519.92, 2 , 0 , 0 , 0 ,,
    4.00    4.00
 -969.26   30.74
    4.00    4.00
 -969.25   30.75
Pier Skew, UpSta & Num, DnSta & Num=  ,9601.36, 2 ,9630.86, 2 , 0 , 0 , 0 ,,
    4.00    4.00
 -969.23   30.77
    4.00    4.00
 -969.22   30.78
Pier Skew, UpSta & Num, DnSta & Num=  ,9712.31, 2 ,9741.81, 2 , 0 , 0 , 0 ,,
    4.00    4.00
 -969.19   30.81
    4.00    4.00
 -969.18   30.82
Pier Skew, UpSta & Num, DnSta & Num=  ,9823.26, 2 ,9852.76, 2 , 0 , 0 , 0 ,,
    4.00    4.00
 -969.16   30.84
    4.00    4.00
 -969.15   30.85
Pier Skew, UpSta & Num, DnSta & Num=  ,9934.20, 2 ,9963.70, 2 , 0 , 0 , 0 ,,
    4.00    4.00
 -969.12   30.88
    4.00    4.00
 -969.11   30.89
Pier Skew, UpSta & Num, DnSta & Num=  ,10045.15, 2 ,10074.65, 2 , 0 , 0 , 0 ,,
    4.00    4.00
 -969.08   30.92
    4.00    4.00
 -969.07   30.93
Pier Skew, UpSta & Num, DnSta & Num=  ,10156.10, 2 ,10185.60, 2 , 0 , 0 , 0 ,,
    4.00    4.00
 -969.05   30.95
    4.00    4.00
 -969.04   30.96
Pier Skew, UpSta & Num, DnSta & Num=  ,10267.04, 2 ,10296.54, 2 , 0 , 0 , 0 ,,
    4.00    4.00
 -969.01   30.99
    4.00    4.00
 -969.00   31.00
Pier Skew, UpSta & Num, DnSta & Num=  ,10377.99, 2 ,10407.49, 2 , 0 , 0 , 0 ,,
    4.00    4.00
 -968.98   31.02
    4.00    4.00
 -968.97   31.03
Pier Skew, UpSta & Num, DnSta & Num=  ,10488.94, 2 ,10518.44, 2 , 0 , 0 , 0 ,,
    4.00    4.00
 -968.94   31.06
    4.00    4.00
 -968.93   31.07
Pier Skew, UpSta & Num, DnSta & Num=  ,10599.88, 2 ,10629.38, 2 , 0 , 0 , 0 ,,
    4.00    4.00
 -968.90   31.10
    4.00    4.00
 -968.89   31.11
Pier Skew, UpSta & Num, DnSta & Num=  ,10710.83, 2 ,10740.33, 2 , 0 , 0 , 0 ,,
    4.00    4.00
 -968.87   31.13
    4.00    4.00
 -968.86   31.14
Pier Skew, UpSta & Num, DnSta & Num=  ,10821.78, 2 ,10851.28, 2 , 0 , 0 , 0 ,,
    4.00    4.00
 -968.83   31.17
    4.00    4.00
 -968.82   31.18
Pier Skew, UpSta & Num, DnSta & Num=  ,10932.72, 2 ,10962.22, 2 , 0 , 0 , 0 ,,
    4.00    4.00
 -968.80   31.20
    4.00    4.00
 -968.79   31.21
Pier Skew, UpSta & Num, DnSta & Num=  ,11043.67, 2 ,11073.17, 2 , 0 , 0 , 0 ,,
    4.00    4.00
 -968.76   31.24
    4.00    4.00
 -968.75   31.25
Pier Skew, UpSta & Num, DnSta & Num=  ,11154.62, 2 ,11184.12, 2 , 0 , 0 , 0 ,,
    4.00    4.00
 -968.72   31.28
    4.00    4.00
 -968.71   31.29
Pier Skew, UpSta & Num, DnSta & Num=  ,11265.56, 2 ,11295.06, 2 , 0 , 0 , 0 ,,
    4.00    4.00
 -968.69   31.31
    4.00    4.00
 -968.68   31.32
Pier Skew, UpSta & Num, DnSta & Num=  ,11376.51, 2 ,11406.01, 2 , 0 , 0 , 0 ,,
    4.00    4.00
 -968.65   31.35
    4.00    4.00
 -968.64   31.36
Pier Skew, UpSta & Num, DnSta & Num=  ,11487.46, 2 ,11516.96, 2 , 0 , 0 , 0 ,,
    4.00    4.00
 -968.62   31.38
    4.00    4.00
 -968.61   31.39
Pier Skew, UpSta & Num, DnSta & Num=  ,11598.40, 2 ,11627.90, 2 , 0 , 0 , 0 ,,
    4.00    4.00
 -968.58   31.42
    4.00    4.00
 -968.57   31.43
Pier Skew, UpSta & Num, DnSta & Num=  ,11709.35, 2 ,11738.85, 2 , 0 , 0 , 0 ,,
    4.00    4.00
 -968.54   31.46
    4.00    4.00
 -968.53   31.47
Pier Skew, UpSta & Num, DnSta & Num=  ,11820.30, 2 ,11849.80, 2 , 0 , 0 , 0 ,,
    4.00    4.00
 -968.51   31.49
    4.00    4.00
 -968.50   31.50
Pier Skew, UpSta & Num, DnSta & Num=  ,11931.24, 2 ,11960.74, 2 , 0 , 0 , 0 ,,
    4.00    4.00
 -968.47   31.53
    4.00    4.00
 -968.46   31.54
Pier Skew, UpSta & Num, DnSta & Num=  ,12042.19, 2 ,12071.69, 2 , 0 , 0 , 0 ,,
    4.00    4.00
 -968.43   31.57
    4.00    4.00
 -968.43   31.57
Pier Skew, UpSta & Num, DnSta & Num=  ,12153.14, 2 ,12182.64, 2 , 0 , 0 , 0 ,,
    4.00    4.00
 -968.40   31.60
    4.00    4.00
 -968.39   31.61
Pier Skew, UpSta & Num, DnSta & Num=  ,12264.08, 2 ,12293.58, 2 , 0 , 0 , 0 ,,
    4.00    4.00
 -968.36   31.64
    4.00    4.00
 -968.35   31.65
Pier Skew, UpSta & Num, DnSta & Num=  ,12375.03, 2 ,12404.53, 2 , 0 , 0 , 0 ,,
    4.00    4.00
 -968.33   31.67
    4.00    4.00
 -968.32   31.68
Pier Skew, UpSta & Num, DnSta & Num=  ,12485.98, 2 ,12515.48, 2 , 0 , 0 , 0 ,,
    4.00    4.00
 -968.29   31.71
    4.00    4.00
 -968.28   31.72
Pier Skew, UpSta & Num, DnSta & Num=  ,12596.92, 2 ,12626.42, 2 , 0 , 0 , 0 ,,
    4.00    4.00
 -968.25   31.75
    4.00    4.00
 -968.24   31.76
Pier Skew, UpSta & Num, DnSta & Num=  ,12707.87, 2 ,12737.37, 2 , 0 , 0 , 0 ,,
    4.00    4.00
 -968.22   31.78
    4.00    4.00
 -968.21   31.79
Pier Skew, UpSta & Num, DnSta & Num=  ,12818.82, 2 ,12848.32, 2 , 0 , 0 , 0 ,,
    4.00    4.00
 -968.18   31.82
    4.00    4.00
 -968.17   31.83
Pier Skew, UpSta & Num, DnSta & Num=  ,12929.76, 2 ,12959.26, 2 , 0 , 0 , 0 ,,
    4.00    4.00
 -968.15   31.85
    4.00    4.00
 -968.14   31.86
Pier Skew, UpSta & Num, DnSta & Num=  ,13040.71, 2 ,13070.21, 2 , 0 , 0 , 0 ,,
    4.00    4.00
 -968.11   31.89
    4.00    4.00
 -968.10   31.90
Pier Skew, UpSta & Num, DnSta & Num=  ,13151.66, 2 ,13181.16, 2 , 0 , 0 , 0 ,,
    4.00    4.00
 -968.07   31.93
    4.00    4.00
 -968.06   31.94
Pier Skew, UpSta & Num, DnSta & Num=  ,13262.60, 2 ,13292.10, 2 , 0 , 0 , 0 ,,
    4.00    4.00
 -968.04   31.96
    4.00    4.00
 -968.03   31.97
Pier Skew, UpSta & Num, DnSta & Num=  ,13373.55, 2 ,13403.05, 2 , 0 , 0 , 0 ,,
    4.00    4.00
 -968.00   32.00
    4.00    4.00
 -967.99   32.01
Pier Skew, UpSta & Num, DnSta & Num=  ,13484.50, 2 ,13514.00, 2 , 0 , 0 , 0 ,,
    4.00    4.00
 -967.97   32.03
    4.00    4.00
 -967.96   32.04
Pier Skew, UpSta & Num, DnSta & Num=  ,13595.44, 2 ,13624.94, 2 , 0 , 0 , 0 ,,
    4.00    4.00
 -967.93   32.07
    4.00    4.00
 -967.92   32.08
Pier Skew, UpSta & Num, DnSta & Num=  ,13706.39, 2 ,13735.89, 2 , 0 , 0 , 0 ,,
    4.00    4.00
 -967.89   32.11
    4.00    4.00
 -967.88   32.12
Pier Skew, UpSta & Num, DnSta & Num=  ,13817.34, 2 ,13846.84, 2 , 0 , 0 , 0 ,,
    4.00    4.00
 -967.86   32.14
    4.00    4.00
 -967.85   32.15
Pier Skew, UpSta & Num, DnSta & Num=  ,13928.28, 2 ,13957.78, 2 , 0 , 0 , 0 ,,
    4.00    4.00
 -967.82   32.18
    4.00    4.00
 -967.81   32.19
Pier Skew, UpSta & Num, DnSta & Num=  ,14039.23, 2 ,14068.73, 2 , 0 , 0 , 0 ,,
    4.00    4.00
 -967.79   32.21
    4.00    4.00
 -967.78   32.22
Pier Skew, UpSta & Num, DnSta & Num=  ,14150.18, 2 ,14179.68, 2 , 0 , 0 , 0 ,,
    4.00    4.00
 -967.75   32.25
    4.00    4.00
 -967.74   32.26
Pier Skew, UpSta & Num, DnSta & Num=  ,14261.12, 2 ,14290.62, 2 , 0 , 0 , 0 ,,
    4.00    4.00
 -967.71   32.29
    4.00    4.00
 -967.70   32.30
Pier Skew, UpSta & Num, DnSta & Num=  ,14372.07, 2 ,14401.57, 2 , 0 , 0 , 0 ,,
    4.00    4.00
 -967.68   32.32
    4.00    4.00
 -967.67   32.33
Pier Skew, UpSta & Num, DnSta & Num=  ,14483.02, 2 ,14512.52, 2 , 0 , 0 , 0 ,,
    4.00    4.00
 -967.64   32.36
    4.00    4.00
 -967.63   32.37
Pier Skew, UpSta & Num, DnSta & Num=  ,14593.96, 2 ,14623.46, 2 , 0 , 0 , 0 ,,
    4.00    4.00
 -967.60   32.40
    4.00    4.00
 -967.60   32.40
Pier Skew, UpSta & Num, DnSta & Num=  ,14704.91, 2 ,14734.41, 2 , 0 , 0 , 0 ,,
    4.00    4.00
 -967.57   32.43
    4.00    4.00
 -967.56   32.44
Pier Skew, UpSta & Num, DnSta & Num=  ,14815.86, 2 ,14845.36, 2 , 0 , 0 , 0 ,,
    4.00    4.00
 -967.53   32.47
    4.00    4.00
 -967.52   32.48
Pier Skew, UpSta & Num, DnSta & Num=  ,14926.80, 2 ,14956.30, 2 , 0 , 0 , 0 ,,
    4.00    4.00
 -967.50   32.50
    4.00    4.00
 -967.49   32.51
Pier Skew, UpSta & Num, DnSta & Num=  ,15037.75, 2 ,15067.25, 2 , 0 , 0 , 0 ,,
    4.00    4.00
 -967.46   32.54
    4.00    4.00
 -967.45   32.55
Pier Skew, UpSta & Num, DnSta & Num=  ,15148.70, 2 ,15178.20, 2 , 0 , 0 , 0 ,,
    4.00    4.00
 -967.42   32.58
    4.00    4.00
 -967.42   32.58
Pier Skew, UpSta & Num, DnSta & Num=  ,15259.64, 2 ,15289.14, 2 , 0 , 0 , 0 ,,
    4.00    4.00
 -967.39   32.61
    4.00    4.00
 -967.38   32.62
Pier Skew, UpSta & Num, DnSta & Num=  ,15370.59, 2 ,15400.09, 2 , 0 , 0 , 0 ,,
    4.00    4.00
 -967.35   32.65
    4.00    4.00
 -967.34   32.66
Pier Skew, UpSta & Num, DnSta & Num=  ,15481.54, 2 ,15511.04, 2 , 0 , 0 , 0 ,,
    4.00    4.00
 -967.32   32.68
    4.00    4.00
 -967.31   32.69
Pier Skew, UpSta & Num, DnSta & Num=  ,15592.48, 2 ,15621.98, 2 , 0 , 0 , 0 ,,
    4.00    4.00
 -967.28   32.72
    4.00    4.00
 -967.27   32.73
Pier Skew, UpSta & Num, DnSta & Num=  ,15703.43, 2 ,15732.93, 2 , 0 , 0 , 0 ,,
    4.00    4.00
 -967.24   32.76
    4.00    4.00
 -967.23   32.77
Pier Skew, UpSta & Num, DnSta & Num=  ,15814.38, 2 ,15843.88, 2 , 0 , 0 , 0 ,,
    4.00    4.00
 -967.21   32.79
    4.00    4.00
 -967.20   32.80
Pier Skew, UpSta & Num, DnSta & Num=  ,15925.32, 2 ,15954.82, 2 , 0 , 0 , 0 ,,
    4.00    4.00
 -967.17   32.83
    4.00    4.00
 -967.16   32.84
BR Coef=-1 , 0 , 0 ,, 0 ,,,0.8,0,1,0,
WSPro=,,,, 1 ,,,, 0 ,,,, 0 ,,,,-1 ,-1 ,-1 , 0 , 0 , 0 , 0 , 0
BC Design=,, 0 ,, 0 ,,,,,,

Type RM Length L Ch R = 1 ,9207.989,1827.535300,1827.535300,1827.535300
XS GIS Cut Line= 6
862808.637995838745316.452193259860263.802571511 740360.08418852
859746.995613427738819.079017683859477.837328911736757.089457454
859314.351489719734833.307142281859492.735216523731583.817899679
#Sta/Elev= 30
6804.85634.485226898.09845.456567722.30928.235437789.28510.483017867.424 9.02518
8124.16517.881929302.0996.6383069944.72720.883899989.8237.39798710046.19 18.8997
12371.945.69650214482.599.59787314562.8720.3746514603.218.41147315823.47 17.5703
15853.727.58863416015.0813.6708516085.6631.1024317541.4623.3123318022.7841.00956
18133.2213.8149118243.66 42.002718468.8743.7259819606.7122.0769920717.7629.67232
20777.8219.6886520847.8833.6122921158.1834.3829421228.2450.6919321269.4680.20769
#Mann= 3 , 0 , 0
6804.856  0.0508       06804.856  0.0508       021269.46  0.0508       0
#XS Ineff= 2 , 0
       08125.412        15720.73       0
Bank Sta=6804.856,21269.46
Exp/Cntr=0.3,0.1

Type RM Length L Ch R = 1 ,7380.454,1230.075600,1230.075600,1230.075600
XS GIS Cut Line= 6
863658.414385148743544.202381642862707.345327099741350.267645328
862080.828072382738890.528104802 860961.40022035735743.675337958
860346.148149721733816.692010883859523.528405848730579.107759556
#Sta/Elev= 30
8643.197107.17438869.95123.803298946.06118.10705  8978.77.2274699054.85518.69895
9164.5676.7066089480.5817.105692  9657.218.432249789.1258.376449    99997.650247
 10046.415.5296110079.738.61667810270.336.43183812350.230.85146113790.878.611731
13843.321.475687 13864.311.6541513906.264.18765514902.232.22782716988.216.198224
17463.4711.8094117505.7221.8683217568.9712.1993317631.9818.5638218157.03 11.2269
18366.2317.2158618595.938.828973 20463.714.2007821524.0830.1924522279.6559.52724
#Mann= 3 , 0 , 0
8643.197  0.0418       08643.197  0.0418       022279.65  0.0418       0
#XS Ineff= 2 , 0
       08895.401        13863.01       0
Bank Sta=8643.197,22279.65
Exp/Cntr=0.3,0.1

Type RM Length L Ch R = 1 ,6150.378,1230.075600,1230.075600,1230.075600
XS GIS Cut Line= 6
 864830.66567337743098.834677772863835.915744453740968.698702361
862169.544110478737842.683445179861325.369026179736030.610132099
860423.971555784733531.320162424859619.282197621 730524.82752844
#Sta/Elev= 30
8422.914162.98998791.94132.597568848.86117.275228939.71514.900728984.9525.508567
9041.49814.374439177.2096.0643049852.8116.0732599948.49412.530949990.6684.618699
 10064.412.0902510505.234.51137912130.631.027414 13460.88.66749713551.561.493029
16714.514.94299317058.5610.13543   1711221.1416117165.4311.5595317250.92 18.1647
17293.6710.94462 17347.118.5214118111.5511.3891118375.2817.5445318511.828.421208
19307.7615.1868119370.349.15001420895.3720.8365121699.5738.0590122090.6959.83423
#Mann= 3 , 0 , 0
8422.914  0.0473       08422.914  0.0473       022090.69  0.0473       0
#XS Ineff= 2 , 0
       0                13281.65       0
Bank Sta=8422.914,22090.69
Exp/Cntr=0.3,0.1

Type RM Length L Ch R = 1 ,4920.302,1230.075600,1230.075600,1230.075600
XS GIS Cut Line= 6
866081.090942669742340.856001723 865303.55543906741232.691932068
 863084.97853834 738609.90011617861999.039210174736952.041401191
860779.646599072734217.607844392859689.611022289730484.960143988
#Sta/Elev= 30
8459.457167.36338615.19893.630428689.44568.035778951.15814.236379067.3822.779654
9104.56611.065139304.7162.4609269862.709 10.313510011.633.64455913469.581.419868
16637.934.68453316933.7810.5949216987.8620.5551917052.7411.4024317117.6318.12889
17193.33 12.858317352.0518.4889717409.6110.1947217496.1316.86796 17646.411.60921
17721.1917.3272317763.9310.98475 18127.218.2914718339.7513.3683418371.4719.49044
18678.127.66807520228.3713.3361221348.1431.1093821410.0326.5667622121.51 59.0322
#Mann= 3 , 0 , 0
8459.457   0.059       08459.457   0.059       022121.51   0.059       0
#XS Ineff= 2 , 0
       0                12985.16       0
Bank Sta=8459.457,22121.51
Exp/Cntr=0.3,0.1

Type RM Length L Ch R = 1 ,3690.227,1230.075700,1230.075700,1230.075700
XS GIS Cut Line= 6
866968.279352309741112.395586639863860.981084499738954.033549363
862423.755023042737333.039376265 861644.28383742735999.047874615
860887.409188381734269.424358695859735.173547632730459.132115967
#Sta/Elev= 30
 9047.6442.470839113.518 39.57919237.16416.801379298.25221.647989323.7179.629275
9397.9042.5059789447.36311.404139609.6742.46124213737.761.32871613765.466.721005
16811.033.55733117121.9910.9471617188.0419.9793817253.5611.4873317319.0718.24932
17706.6112.3737517756.4318.0770217863.82 10.088717896.1117.6178117992.9710.83656
18516.9218.8355618583.2913.9867118615.1920.3272718657.72 13.462718899.3812.66644
 18928.819.3031219008.617.69707720531.7513.5224222056.0436.8711622433.8859.80906
#Mann= 3 , 0 , 0
 9047.64  0.0548       0 9047.64  0.0548       022433.88  0.0548       0
#XS Ineff= 2 , 0
       09550.969        13002.08       0
Bank Sta=9047.64,22433.88
Exp/Cntr=0.3,0.1

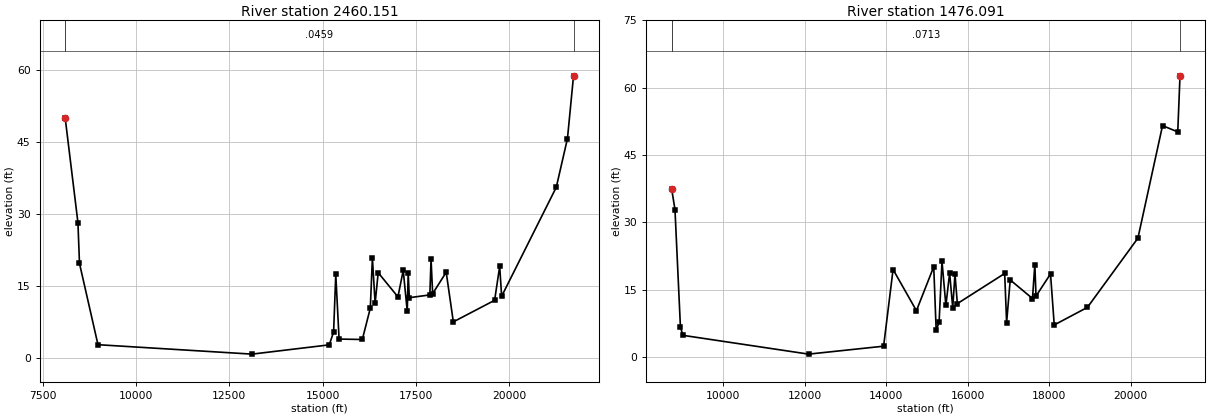
Type RM Length L Ch R = 1 ,2460.151,984.060500,984.060500,984.060500
XS GIS Cut Line= 6
868069.092214571 739742.53969172864893.095879881739065.263595019
863782.698602066 738425.36338703862894.484384535737584.319235518
861080.802906431734472.901765115859791.592348199730427.150051262
#Sta/Elev= 30
8096.63449.915158437.93828.21628 8479.7519.727918975.547 2.84117 13107.70.882334
15179.632.80859915296.165.48494615354.4317.4540515442.944.01346916066.363.922277
16280.95 10.438416336.5120.8360116409.86 11.439616492.0817.80873   1702212.78102
17163.82 18.285917271.829.75981517296.8417.6953517327.4612.6084917877.8313.18923
17910.07 20.625217953.0613.4480118316.6717.9015718507.737.58463719615.2312.06824
19751.3419.1292519803.4912.9029321269.4635.5610221569.2245.6848621732.1458.71573
#Mann= 3 , 0 , 0
8096.634  0.0459       08096.634  0.0459       021732.14  0.0459       0
#XS Ineff= 2 , 0
       08964.379        12184.62       0
Bank Sta=8096.634,21732.14
Exp/Cntr=0.3,0.1

Type RM Length L Ch R = 1 ,1476.091,1476.090700,1476.090700,1476.090700
XS GIS Cut Line= 6
867733.533965804 738699.16781567864582.897945078738003.355542776
863554.199195349737396.001347342862798.309776917736674.654064721
861141.538563937733909.361225611859942.041276993730341.865552563
#Sta/Elev= 30
8730.75837.424168811.79232.857188945.9066.6593339007.4634.84091112092.490.654247
13934.162.42111414166.3419.5027314739.5910.3334615164.7720.1201715224.26 6.01108
15295.927.72959515367.4521.3059915462.8311.4949515554.8518.7274715630.8211.01432
15686.5418.4905115744.2711.9024816906.3318.6178416954.027.67852617041.98 17.1813
17589.0913.0431217646.6720.6118917675.4913.5752618031.8818.5237418123.337.151646
18938.5211.0734620177.4826.4865620781.9351.55038 21155.6 50.155421210.7562.64409
#Mann= 3 , 0 , 0
8730.758  0.0713       08730.758  0.0713       021210.75  0.0713       0
#XS Ineff= 2 , 0
       09182.975           11647       0
Bank Sta=8730.758,21210.75
Exp/Cntr=0.3,0.1