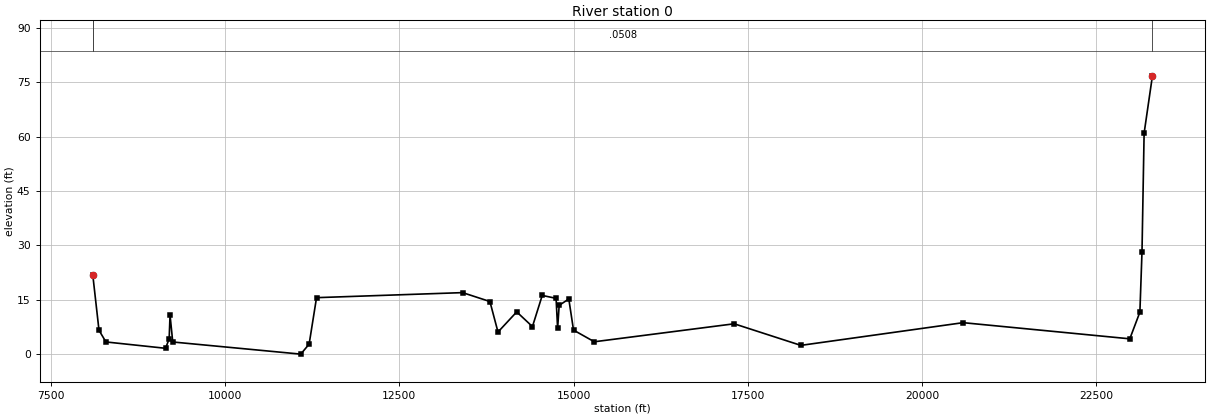
HEC-RAS study 8407_ras.prj: 8407

--- 8407_ras.g01 (geometry) --- (continued)

Type RM Length L Ch R = 1 ,       0,0.000000,0.000000,0.000000
XS GIS Cut Line= 6
867844.168757163738584.122003126866236.954007085736355.141831524
864833.388389497737381.174767721862769.963708906736205.926754048
865229.982123176735275.200845645864280.786917123730656.846817438
#Sta/Elev= 30
8102.78821.865188191.9756.5799248291.3673.3576659146.7841.6085239198.3954.201751
9211.29810.755729250.0063.34822811086.51       011206.592.76043111312.7715.56932
13408.38 16.957213800.0814.5039113915.916.09058114184.5411.6485314410.187.593919
14550.6316.18339 14749.315.3831514771.417.06969214793.5313.4501714931.7815.20543
14999.38 6.63106 15297.53.40729217304.298.36457618260.63 2.4150320588.88 8.67387
22979.794.22108423124.4511.5756323154.7528.2229423185.0660.91144 23304.476.73416
#Mann= 3 , 0 , 0
8102.788  0.0508       08102.788  0.0508       0 23304.4  0.0508       0
#XS Ineff= 2 , 0
       08550.205        10766.82       0
Bank Sta=8102.788,23304.4
Exp/Cntr=0.3,0.1